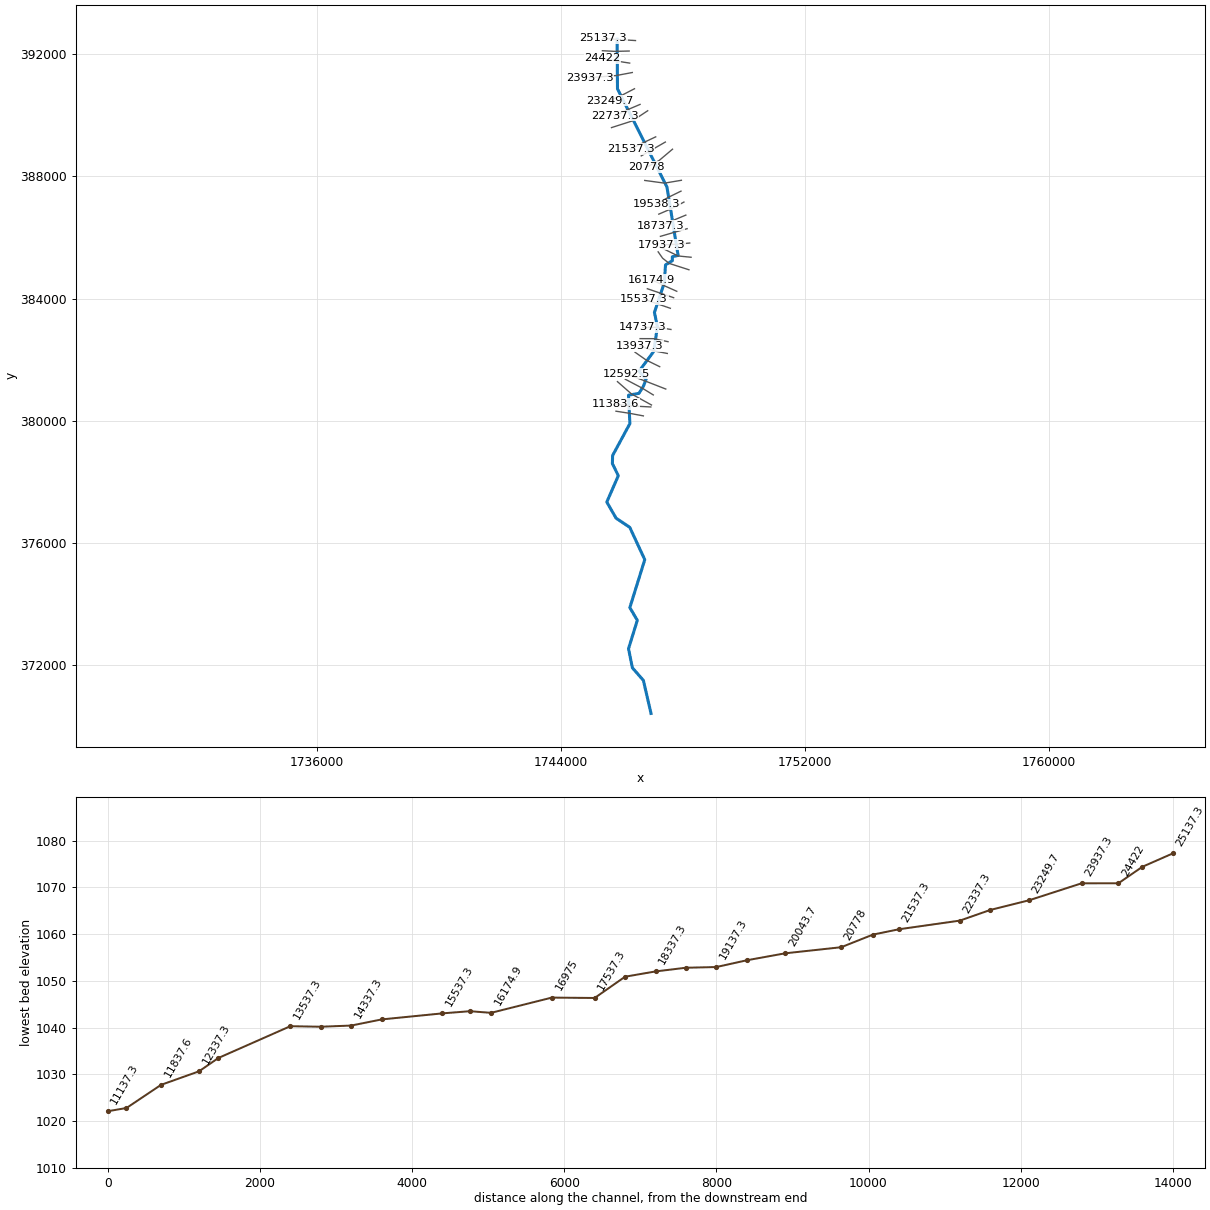
--- PlmRn.prj (project) ---

Proj Title=PlmRn
Current Plan=p01
Geom File=g01
Flow File=f01
Plan File=p01
DSS Export Rating Curves=0
DSS Export Rating Curve Sorted=0
DSS Export Volume Flow Curves=0
DXF OffsetX=0
DXF OffsetY=0
DXF ScaleX=0
DXF ScaleY=0

--- PlmRn.p01 (plan) ---

Plan Title=Floodplain
Program Version=4.00
Geom File=g01
Flow File=f01
K Sum by GR=0
Std Step Tol=0.01
Critical Tol=0.01
Num of Std Step Trials=20
Max Error Tol=0.3
Flow Tol Ratio=0.001
Split Flow NTrial=30
Split Flow Tol=0.02
Split Flow Ratio=0.02
Log Output Level=0
Friction Slope Method=1
Unsteady Friction Slope Method=2
Unsteady Bridges Friction Slope Method=1
Global Log Level=0
CheckData=False
Run HTab=0
Run UNet=0
Run PostProcess=0
UNET Theta=0
UNET Theta Warmup=0
UNET ZTol=0
UNET ZSATol=0
UNET MxIter=0
UNET MaxInSteps=0
UNET DtIC=0
UNET DtMin=0
UNET MaxCRTS=0
UNET WFStab=0
UNET SFStab=0
UNET WFX=0
UNET SFX=0
UNET DSS MLevel=0
UNET DZMax Abort=0
UNET Convert EG Bridges=0
UNET Use Existing IB Tables=0
UNET Froude Limit=0
UNET Froude Power=0
Write IC File=0
Echo Input=False
Echo Output=False
Write Detailed=0

--- PlmRn.f01 (steady flow) ---

Flow Title=NFF Regression Equation
Program Version=4.00
Number of Profiles=1
Profile Names=P100yr
River Rch & RM=PlmRn,Main      ,25137.3
936.6864
River Rch & RM=PlmRn,Main      ,23249.7
950.9706
River Rch & RM=PlmRn,Main      ,23249.7
1147.045
River Rch & RM=PlmRn,Main      ,20043.7
1232.403
River Rch & RM=PlmRn,Main      ,19538.3
1557.898
River Rch & RM=PlmRn,Main      ,18337.3
1622.894
River Rch & RM=PlmRn,Main      ,16174.9
1791.986
River Rch & RM=PlmRn,Main      ,12592.5
1889.262
River Rch & RM=PlmRn,Main      ,5972.5
2072.160
River Rch & RM=PlmRn,Main      ,337.3
2301.417
Boundary for River Rch & Prof#=PlmRn,Main      ,1
Up Type=0
Dn Type=3
Dn Slope=0.007732

--- PlmRn.g01 (geometry) ---

Geom Title=USGS 3m DEM
Program Version=4.00

River Reach=PlmRn     ,Main
Reach XY= 30
     1745851.270      392495.177     1745864.399      390865.608
     1747486.071      387650.451     1747850.685      385411.963
     1747660.939      385367.271     1747660.704      385237.271
     1747438.435      385100.415     1747398.957      384514.684
     1747074.757      383543.939     1747173.276      383079.250
     1747050.926      382267.092     1746570.305      381615.734
     1746802.512      381355.346     1746711.026      381122.340
     1746568.248      380895.217     1746224.950      380833.440
     1746270.489      379902.270     1745704.224      378858.073
     1745697.291      378591.170     1745891.703      378197.503
     1745513.837      377333.560     1745818.470      376804.831
     1746267.307      376504.617     1746758.369      375446.688
     1746268.840      373875.698     1746513.998      373460.953
     1746225.774      372529.597     1746352.482      371905.043
     1746712.514      371493.018     1746962.732      370412.379

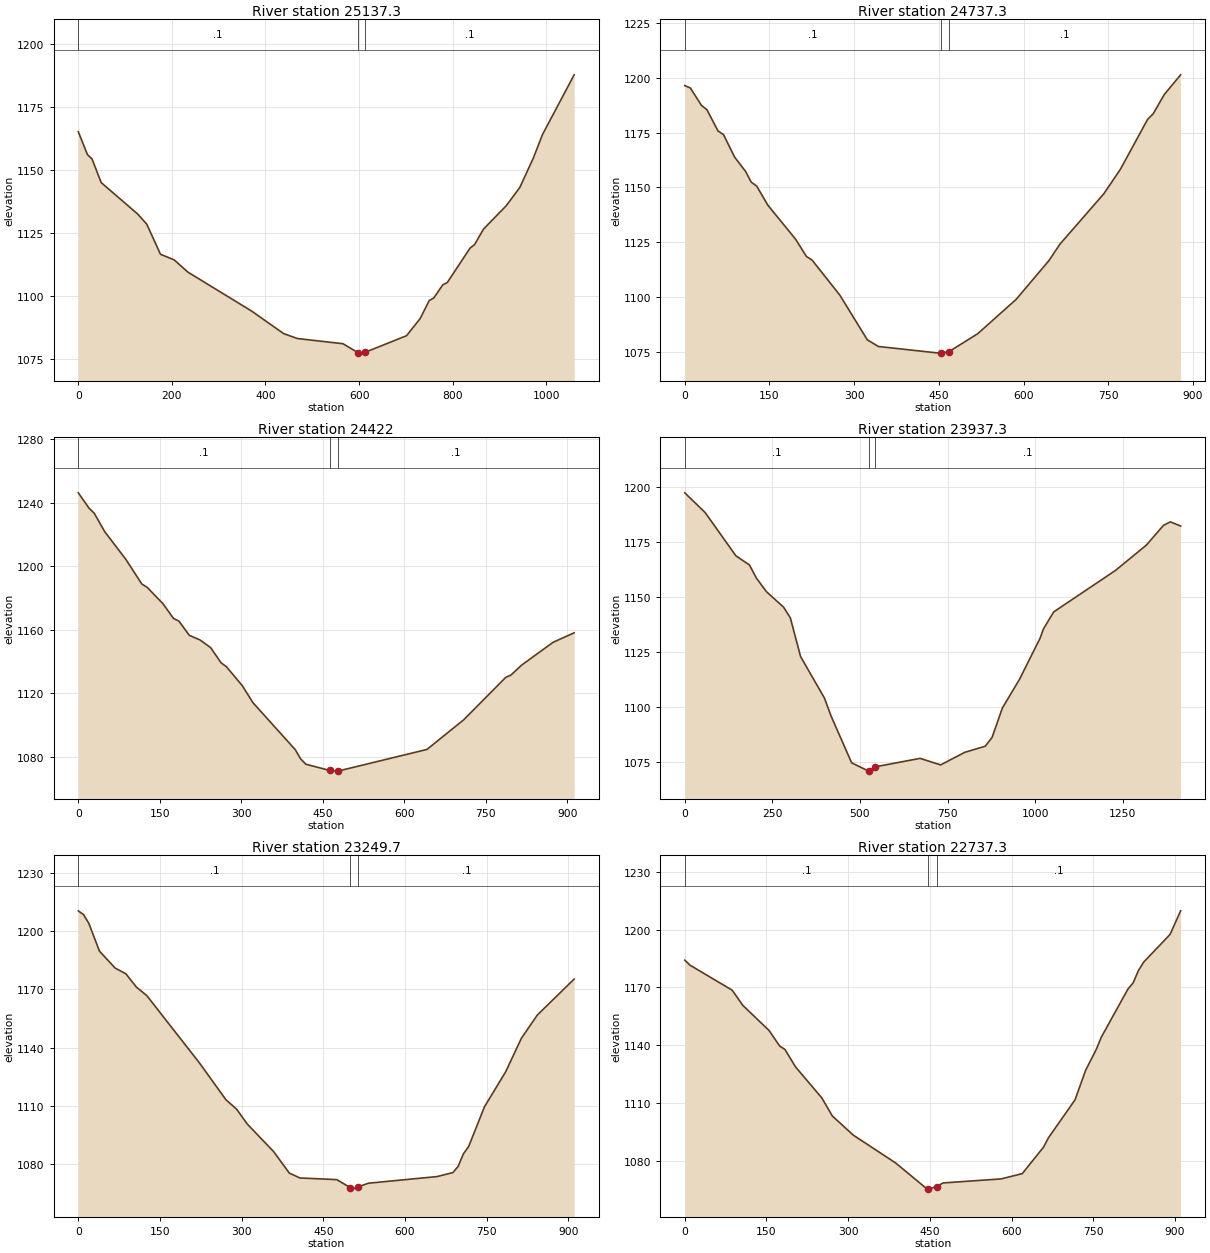
Type RM Length L Ch R = 1 ,25137.3,398.019,400,400.627
XS GIS Cut Line= 3
     1746454.096      392448.450     1745850.483      392485.208
     1745396.895      392521.027
#Sta/Elev= 30
       0 1165.12    19.5 1156.10    29.3 1154.35    48.8 1144.99   126.8 1132.49
   146.3 1128.47   175.6 1116.50   204.8 1114.29   234.1 1109.42   370.6 1093.93
   438.9 1084.99   468.2 1083.05   565.7 1080.98   597.2 1077.48   604.7 1077.25
   612.2 1077.52   701.5 1084.17   730.6 1090.98   749.9 1098.12   759.6 1099.14
   779.0 1104.39   788.7 1105.31   837.1 1118.93   846.8 1120.35   866.1 1126.54
   914.5 1135.78   943.6 1143.05   972.6 1154.78   992.0 1164.05  1059.7 1187.77
#Mann= 3 , 0 , 0
       0     0.1       0   597.2   0.045       0   612.2     0.1       0
Bank Sta=   597.2,   612.2
Exp/Cntr=0.3,0.1

Type RM Length L Ch R = 1 ,24737.3,319.751,315.305,312.247
XS GIS Cut Line= 3
     1746247.206      392105.526     1745786.908      392094.031
     1745369.751      392115.028
#Sta/Elev= 30
       0 1196.43     9.8 1195.36    29.4 1187.46    39.2 1185.43    58.8 1175.75
    68.6 1174.06    88.2 1163.82   107.8 1157.24   117.6 1152.39   127.4 1150.58
   146.9 1141.95   195.9 1126.47   215.5 1118.48   225.3 1116.87   274.3 1100.95
   323.3 1080.45   342.9 1077.42   450.6 1074.39   452.9 1074.40   467.9 1075.06
   518.7 1083.24   586.7 1098.88   645.0 1116.64   664.4 1124.12   742.1 1147.09
   771.3 1158.20   819.8 1181.10   829.6 1183.60   849.0 1192.31   878.1 1201.35
#Mann= 3 , 0 , 0
       0     0.1       0   452.9   0.045       0   467.9     0.1       0
Bank Sta=   452.9,   467.9
Exp/Cntr=0.3,0.1

Type RM Length L Ch R = 1 ,24422,476.5,484.695,490.799
XS GIS Cut Line= 3
     1746263.457      391709.869     1745811.065      391780.044
     1745364.083      391865.712
#Sta/Elev= 30
       0 1246.18    19.5 1236.62    29.2 1233.35    48.7 1221.67    87.7 1204.18
   116.9 1188.73   126.6 1186.71   155.8 1176.33   175.3 1167.04   185.1 1165.40
   204.5 1156.37   224.0 1153.51   243.5 1148.69   263.0 1139.03   272.7 1136.64
   302.0 1124.63   321.4 1114.03   399.4 1084.39   409.1 1078.68   418.8 1075.22
   463.1 1071.27   477.2 1070.86   478.1 1070.90   641.8 1084.51   709.6 1103.22
   787.0 1129.94   796.7 1131.41   816.1 1137.63   874.2 1152.04   912.9 1158.00
#Mann= 3 , 0 , 0
       0     0.1       0   463.1   0.045       0   478.1     0.1       0
Bank Sta=   463.1,   478.1
Exp/Cntr=0.3,0.1

Type RM Length L Ch R = 1 ,23937.3,682.869,687.634,694.863
XS GIS Cut Line= 3
     1746349.720      391401.796     1745824.455      391302.276
     1744946.451      391233.636
#Sta/Elev= 30
       0 1197.27    58.3 1188.27   145.8 1168.67   184.7 1164.48   204.1 1158.60
   233.3 1152.32   281.9 1145.35   301.3 1140.46   330.5 1122.90   398.5 1104.07
   418.0 1095.70   476.3 1074.62   524.9 1070.85   527.1 1070.92   542.1 1072.75
   671.6 1076.65   730.3 1073.67   798.8 1079.37   857.5 1082.16   877.1 1086.15
   906.5 1099.52   955.4 1112.54  1014.1 1131.21  1023.9 1135.51  1053.2 1143.19
  1229.4 1162.02  1317.4 1173.50  1366.4 1182.49  1385.9 1184.09  1415.3 1182.19
#Mann= 3 , 0 , 0
       0     0.1       0   527.1   0.045       0   542.1     0.1       0
Bank Sta=   527.1,   542.1
Exp/Cntr=0.3,0.1

Type RM Length L Ch R = 1 ,23249.7,512.371,512.366,513.426
XS GIS Cut Line= 3
     1746421.169      390870.304     1746016.482      390661.339
     1745596.716      390484.861
#Sta/Elev= 30
       0 1210.50     9.7 1208.51    19.4 1203.99    38.8 1189.76    67.8 1181.00
    87.2 1178.12   106.6 1171.27   126.0 1166.79   222.9 1132.05   271.3 1113.18
   290.7 1108.42   310.1 1100.81   358.5 1086.63   387.6 1075.50   407.0 1072.98
   474.8 1072.12   499.4 1068.04   503.9 1067.23   514.4 1068.45   533.0 1070.28
   658.9 1073.69   688.0 1075.75   697.7 1078.96   707.4 1085.42   717.0 1089.15
   746.1 1109.65   784.9 1127.58   813.9 1144.90   843.0 1156.81   910.8 1175.38
#Mann= 3 , 0 , 0
       0     0.1       0   499.4   0.045       0   514.4     0.1       0
Bank Sta=   499.4,   514.4
Exp/Cntr=0.3,0.1

Type RM Length L Ch R = 1 ,22737.3,395.726,400,396.906
XS GIS Cut Line= 3
     1746604.441      390356.846     1746185.442      390179.741
     1745774.633      389982.703
#Sta/Elev= 30
       0 1184.12     9.7 1181.48    87.1 1168.48   106.5 1160.63   154.9 1147.52
   174.2 1139.49   183.9 1137.71   203.2 1128.71   251.6 1112.54   271.0 1103.13
   309.7 1093.14   387.1 1078.77   445.2 1065.15   447.4 1065.18   462.4 1066.50
   474.3 1068.36   580.9 1070.46   619.7 1073.20   658.5 1086.87   668.2 1091.99
   716.6 1111.53   736.0 1126.83   755.4 1137.64   765.1 1144.22   813.6 1169.01
   823.3 1172.29   833.0 1178.69   842.7 1183.09   891.1 1197.47   910.5 1209.73
#Mann= 3 , 0 , 0
       0     0.1       0   447.4   0.045       0   462.4     0.1       0
Bank Sta=   447.4,   462.4
Exp/Cntr=0.3,0.1

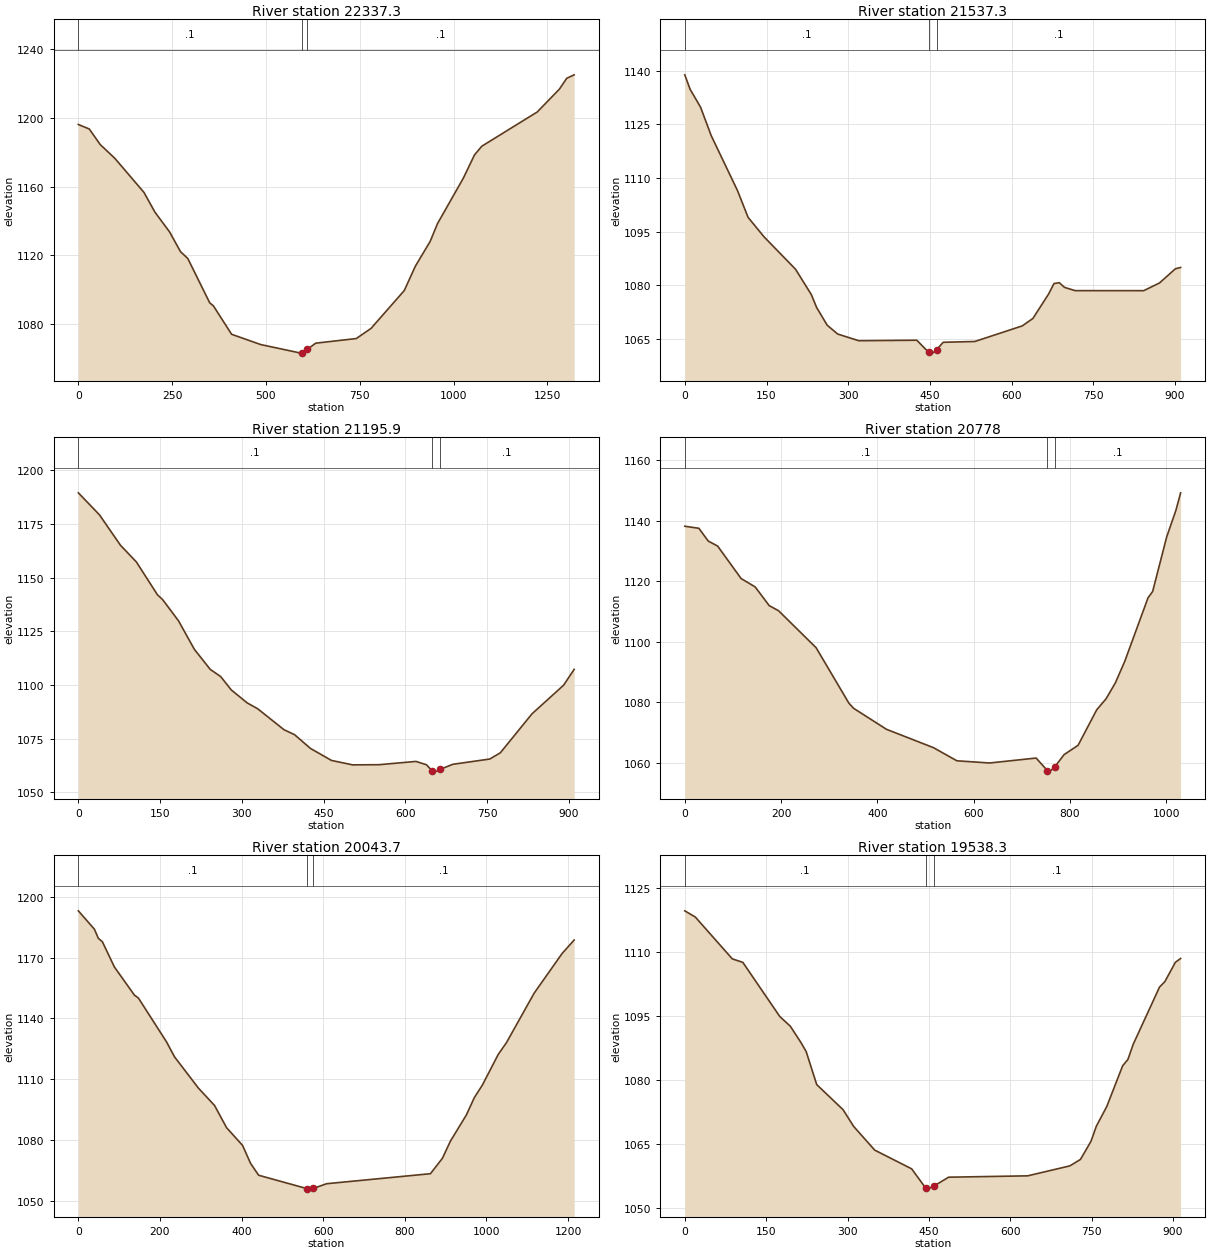
Type RM Length L Ch R = 1 ,22337.3,803.359,800,803.55
XS GIS Cut Line= 3
     1746854.202      390149.291     1746351.686      389816.225
     1745667.644      389597.231
#Sta/Elev= 30
       0 1196.18    29.2 1193.53    58.3 1184.48    97.2 1176.46   175.0 1156.54
   204.2 1145.03   243.1 1133.56   272.3 1122.00   291.7 1118.04   350.1 1092.19
   359.8 1090.44   408.4 1073.86   486.2 1067.85   593.1 1062.87   595.4 1063.02
   610.4 1065.09   632.4 1068.67   740.6 1071.37   780.0 1077.30   868.5 1099.37
   898.0 1113.55   937.4 1127.99   957.1 1138.41  1025.9 1164.91  1055.5 1178.41
  1075.1 1183.51  1222.7 1203.45  1281.8 1216.78  1301.4 1223.11  1321.1 1225.12
#Mann= 3 , 0 , 0
       0     0.1       0   595.4   0.045       0   610.4     0.1       0
Bank Sta=   595.4,   610.4
Exp/Cntr=0.3,0.1

Type RM Length L Ch R = 1 ,21537.3,339.608,341.4,342.585
XS GIS Cut Line= 3
     1747116.842      389294.564     1746705.323      389100.542
     1746298.980      388895.374
#Sta/Elev= 30
       0 1138.82     9.7 1134.80    29.0 1129.76    48.4 1121.85    96.8 1106.44
   116.2 1098.97   145.2 1093.58   203.3 1084.47   232.3 1077.38   242.0 1073.78
   261.4 1068.83   280.7 1066.35   319.4 1064.49   425.9 1064.63   447.5 1061.28
   455.0 1061.02   462.5 1062.01   474.3 1064.05   532.4 1064.27   619.6 1068.64
   639.0 1070.71   668.0 1077.58   677.7 1080.47   687.4 1080.71   697.1 1079.40
   716.5 1078.49   842.4 1078.48   871.4 1080.63   900.5 1084.59   910.2 1084.97
#Mann= 3 , 0 , 0
       0     0.1       0   447.5   0.045       0   462.5     0.1       0
Bank Sta=   447.5,   462.5
Exp/Cntr=0.3,0.1

Type RM Length L Ch R = 1 ,21195.9,418.519,417.859,417.2
XS GIS Cut Line= 3
     1747432.831      389124.393     1747038.014      388898.241
     1746643.197      388672.089
#Sta/Elev= 30
       0 1189.48    38.7 1179.27    77.4 1165.04   106.5 1157.30   145.2 1142.01
   154.9 1139.71   183.9 1129.86   213.0 1116.59   242.0 1107.29   261.4 1103.88
   280.7 1097.69   309.8 1091.67   329.1 1088.94   377.6 1079.14   396.9 1076.84
   426.0 1070.46   464.7 1064.85   503.4 1062.80   551.8 1062.87   619.6 1064.40
   638.9 1062.86   649.2 1060.05   658.3 1059.88   664.2 1060.74   687.3 1063.06
   755.1 1065.51   774.5 1068.41   832.6 1086.56   890.6 1099.89   910.0 1107.27
#Mann= 3 , 0 , 0
       0     0.1       0   649.2   0.045       0   664.2     0.1       0
Bank Sta=   649.2,   664.2
Exp/Cntr=0.3,0.1

Type RM Length L Ch R = 1 ,20778,744.525,734.336,717.916
XS GIS Cut Line= 3
     1747667.827      388890.284     1747228.497      388519.766
     1746827.311      388305.328
#Sta/Elev= 30
       0 1138.20    29.2 1137.53    48.7 1133.30    68.2 1131.65   116.9 1120.91
   146.1 1118.13   175.3 1111.94   194.8 1110.24   272.7 1098.01   340.9 1079.63
   350.7 1077.95   418.9 1071.01   516.3 1064.95   565.0 1060.60   632.8 1059.87
   729.6 1061.51   752.9 1057.36   758.6 1057.18   767.9 1058.52   787.6 1062.64
   816.7 1065.73   855.4 1077.48   874.8 1081.12   894.1 1086.39   913.5 1093.47
   961.9 1114.52   971.5 1116.61  1000.6 1134.64  1019.9 1143.52  1029.6 1149.26
#Mann= 3 , 0 , 0
       0     0.1       0   752.9   0.045       0   767.9     0.1       0
Bank Sta=   752.9,   767.9
Exp/Cntr=0.3,0.1

Type RM Length L Ch R = 1 ,20043.7,494.559,505.411,523.92
XS GIS Cut Line= 3
     1747958.761      387872.018     1747406.892      387778.786
     1746757.314      387866.630
#Sta/Elev= 30
       0 1193.06    39.3 1184.04    49.1 1179.48    58.9 1177.85    88.4 1165.37
   137.5 1151.50   147.3 1150.06   216.0 1128.51   235.7 1121.11   294.6 1105.61
   333.8 1097.13   363.3 1086.18   402.6 1077.40   422.2 1068.55   441.9 1062.73
   561.1 1056.09   569.5 1055.88   576.1 1056.24   608.6 1058.55   863.0 1063.48
   892.3 1071.08   911.9 1079.52   951.0 1092.43   970.6 1101.01   990.2 1107.15
  1029.3 1122.34  1048.9 1127.95  1117.3 1152.52  1185.8 1172.06  1215.2 1178.68
#Mann= 3 , 0 , 0
       0     0.1       0   561.1   0.045       0   576.1     0.1       0
Bank Sta=   561.1,   576.1
Exp/Cntr=0.3,0.1

Type RM Length L Ch R = 1 ,19538.3,401.457,400.994,397.172
XS GIS Cut Line= 3
     1747945.999      387516.637     1747535.128      387315.990
     1747136.377      387092.774
#Sta/Elev= 30
       0 1119.73    19.5 1118.26    87.6 1108.45   107.0 1107.63   175.1 1094.93
   194.6 1092.63   214.0 1088.84   223.8 1086.69   243.2 1078.94   291.9 1073.03
   311.3 1069.12   350.2 1063.55   418.3 1059.15   444.1 1054.65   447.5 1054.39
   459.1 1055.10   486.4 1057.19   632.3 1057.51   710.0 1059.85   729.5 1061.36
   748.9 1065.61   758.7 1069.13   778.1 1073.80   807.3 1083.35   817.0 1084.83
   826.7 1088.37   875.3 1101.83   885.1 1103.10   904.5 1107.64   914.2 1108.55
#Mann= 3 , 0 , 0
       0     0.1       0   444.1   0.045       0   459.1     0.1       0
Bank Sta=   444.1,   459.1
Exp/Cntr=0.3,0.1

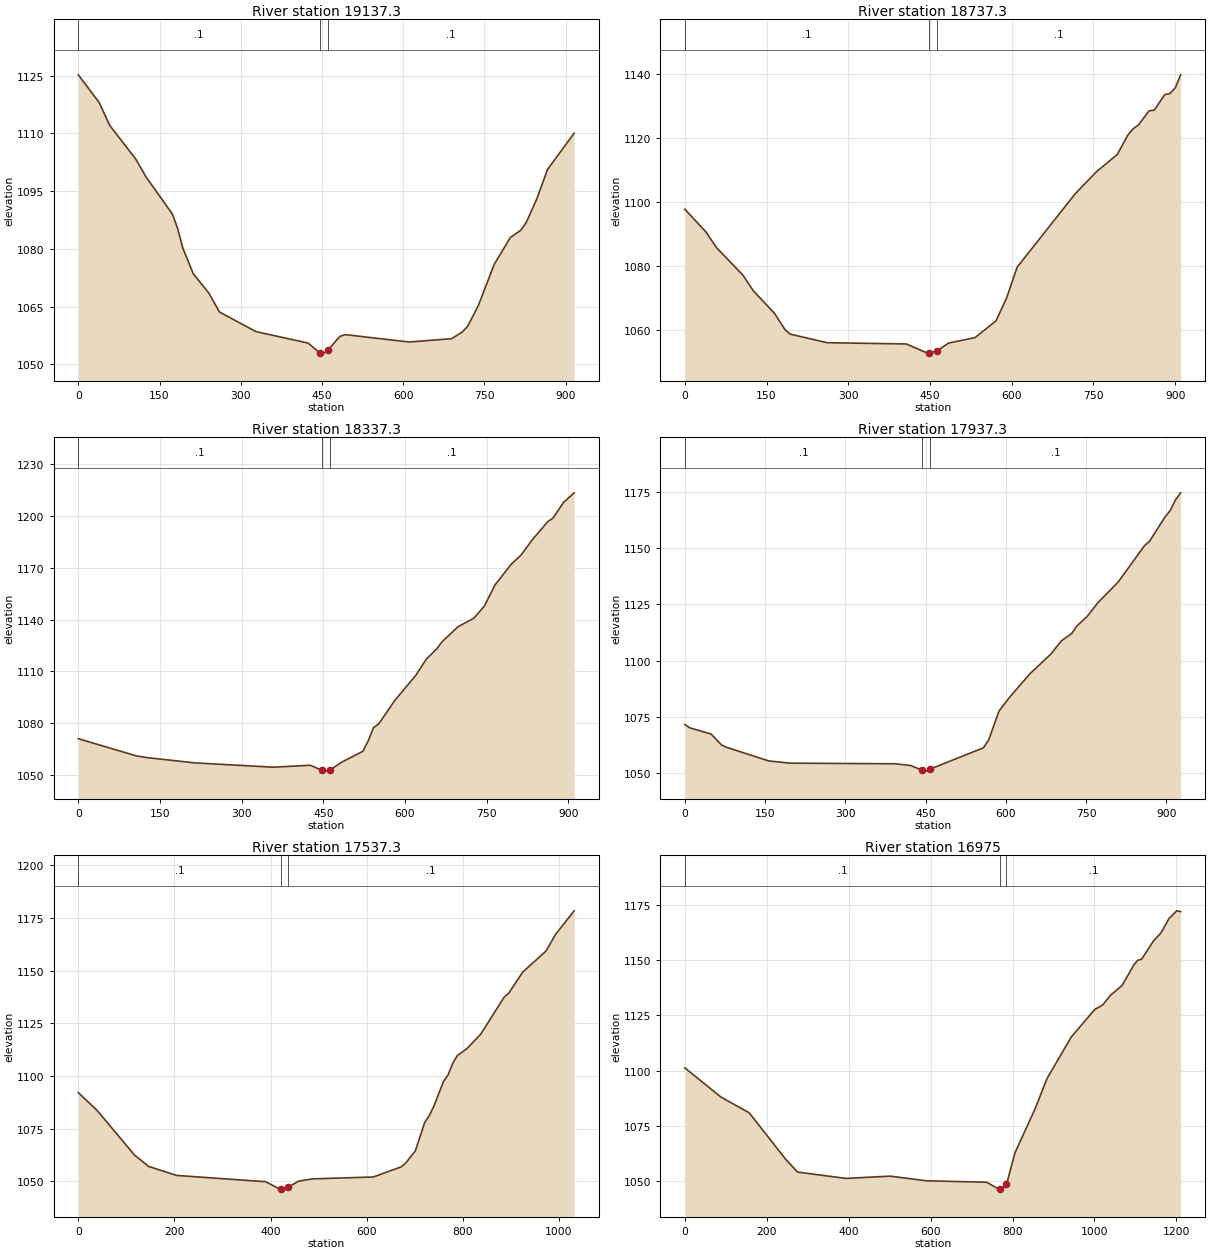
Type RM Length L Ch R = 1 ,19137.3,401.763,400,400.169
XS GIS Cut Line= 3
     1748042.354      387158.941     1747642.416      386945.201
     1747217.639      386762.854
#Sta/Elev= 30
       0 1125.21    38.6 1118.00    57.9 1112.08   106.1 1103.33   125.4 1098.62
   173.7 1089.07   183.3 1085.36   193.0 1080.20   212.3 1073.54   241.2 1068.50
   260.5 1063.63   328.0 1058.53   424.5 1055.55     446 1052.98   453.5 1052.94
     461 1053.70   483.0 1057.29   492.8 1057.75   610.8 1055.83   689.5 1056.69
   709.2 1058.45   719.0 1059.90   738.7 1065.28   768.2 1076.03   797.7 1082.94
   817.4 1084.88   827.2 1086.86   846.9 1093.05   866.6 1100.65   915.7 1110.06
#Mann= 3 , 0 , 0
       0     0.1       0     446   0.045       0     461     0.1       0
Bank Sta=     446,     461
Exp/Cntr=0.3,0.1

Type RM Length L Ch R = 1 ,18737.3,403.206,400,396.967
XS GIS Cut Line= 3
     1748104.521      386731.574     1747684.211      386557.318
     1747263.902      386383.063
#Sta/Elev= 30
       0 1097.78    38.7 1090.70    58.1 1085.78   106.5 1077.20   125.9 1072.26
   164.6 1065.23   183.9 1060.13   193.6 1058.72   261.4 1056.05   406.6 1055.65
   445.3 1052.79   447.5 1052.81   462.5 1053.42   484.0 1055.93   532.4 1057.62
   571.2 1062.87   590.5 1069.99   609.9 1079.64   716.4 1102.58   755.1 1109.41
   793.8 1114.90   813.2 1120.98   822.9 1122.93   832.6 1124.11   851.9 1128.49
   861.6 1128.75   881.0 1133.60   890.6 1133.96   900.3 1135.75   910.0 1139.78
#Mann= 3 , 0 , 0
       0     0.1       0   447.5   0.045       0   462.5     0.1       0
Bank Sta=   447.5,   462.5
Exp/Cntr=0.3,0.1

Type RM Length L Ch R = 1 ,18337.3,403.787,400,394.451
XS GIS Cut Line= 3
     1748147.117      386286.505     1747709.335      386163.007
     1747271.673      386035.888
#Sta/Elev= 30
       0 1070.82   106.5 1060.85   125.8 1059.87   212.9 1056.80   358.1 1054.28
   425.8 1055.40   447.4 1052.52   454.9 1052.00   462.4 1052.68   484.0 1057.25
   522.7 1063.55   532.4 1069.55   542.1 1077.20   551.8 1079.46   580.9 1092.91
   619.7 1107.58   639.1 1117.03   658.5 1123.06   668.2 1127.15   697.3 1135.82
   726.4 1140.74   745.8 1147.85   765.2 1160.04   794.3 1171.80   813.6 1177.58
   833.0 1186.00   862.1 1196.79   871.8 1198.87   891.2 1207.99   910.6 1213.52
#Mann= 3 , 0 , 0
       0     0.1       0   447.4   0.045       0   462.4     0.1       0
Bank Sta=   447.4,   462.4
Exp/Cntr=0.3,0.1

Type RM Length L Ch R = 1 ,17937.3,406.054,400,389.303
XS GIS Cut Line= 3
     1748232.792      385817.050     1747783.401      385773.652
     1747308.619      385761.405
#Sta/Elev= 30
       0 1071.57     9.8 1070.08    49.1 1067.37    68.7 1062.47    78.5 1061.42
   157.0 1055.39   196.3 1054.42   392.6 1054.14   422.0 1053.37     444 1051.21
   451.5 1050.87     459 1051.85   558.1 1061.24   567.8 1064.79   587.2 1077.63
   606.6 1083.64   645.3 1094.27   684.1 1102.92   703.5 1108.78   722.9 1112.05
   732.6 1115.41   752.0 1119.68   771.3 1125.61   810.1 1135.04   858.6 1151.01
   868.3 1153.04   897.3 1163.87   907.0 1166.70   916.7 1171.43   926.4 1174.59
#Mann= 3 , 0 , 0
       0     0.1       0     444   0.045       0     459     0.1       0
Bank Sta=     444,     459
Exp/Cntr=0.3,0.1

Type RM Length L Ch R = 1 ,17537.3,571.346,562.297,557.514
XS GIS Cut Line= 3
     1748276.480      385351.220     1747849.563      385393.268
     1747308.602      385658.861
#Sta/Elev= 30
       0 1092.14    39.0 1083.71   117.0 1062.47   146.2 1057.10   204.7 1052.82
   390.0 1049.83   419.2 1046.32   421.5 1046.39   436.5 1047.22   458.1 1050.10
   487.3 1051.19   613.7 1052.08   672.0 1056.92   681.7 1058.87   701.1 1064.43
   720.6 1077.95   730.3 1081.28   740.0 1085.84   759.5 1097.33   769.2 1100.53
   778.9 1106.03   788.6 1109.74   808.1 1112.94   837.2 1119.89   885.8 1137.42
   895.5 1139.36   924.7 1149.41   973.3 1159.43   992.7 1167.23  1031.6 1178.46
#Mann= 3 , 0 , 0
       0     0.1       0   421.5   0.045       0   436.5     0.1       0
Bank Sta=   421.5,   436.5
Exp/Cntr=0.3,0.1

Type RM Length L Ch R = 1 ,16975,794.927,800.113,805.257
XS GIS Cut Line= 4
     1748206.593      384941.134     1747560.985      385148.707
     1747344.568      385318.270     1747196.634      385528.822
#Sta/Elev= 30
       0 1101.23    88.5 1088.00   157.3 1080.90   245.7 1060.03   275.2 1054.10
   393.1 1051.25   501.2 1052.27   589.7 1050.17   737.1 1049.51   766.5 1046.40
   769.2 1046.46   776.3 1046.62   784.2 1048.59   786.2 1049.09   805.8 1062.73
   854.9 1082.59   884.4 1096.46   943.3 1115.15  1000.7 1127.62  1019.8 1129.62
  1038.9 1134.01  1067.5 1138.47  1096.0 1147.71  1105.6 1149.90  1115.1 1150.34
  1143.7 1158.50  1162.8 1162.34  1181.8 1168.65  1200.9 1172.23  1210.4 1171.89
#Mann= 3 , 0 , 0
       0     0.1       0   769.2   0.045       0   784.2     0.1       0
Bank Sta=   769.2,   784.2
Exp/Cntr=0.3,0.1

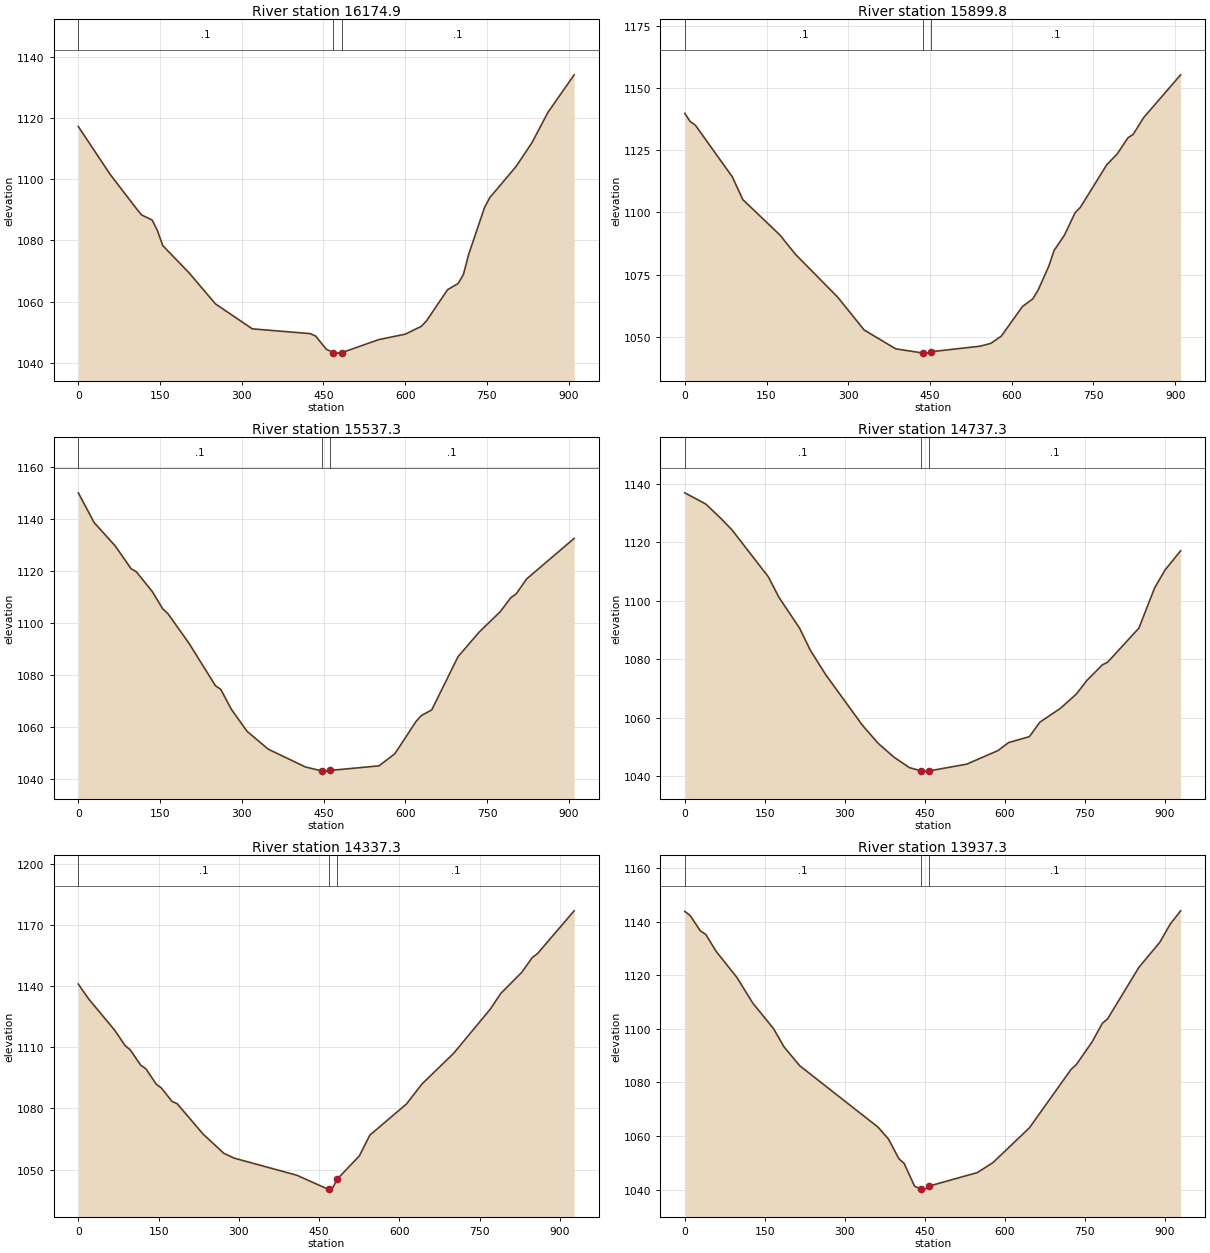
Type RM Length L Ch R = 1 ,16174.9,272.615,275.143,277.712
XS GIS Cut Line= 3
     1747807.471      384236.446     1747391.851      384421.540
     1746980.560      384616.490
#Sta/Elev= 30
       0 1117.19    58.1 1101.63   106.5 1090.40   116.2 1088.29   135.5 1086.63
   145.2 1083.19   154.9 1078.30   203.3 1069.37   251.7 1059.23   319.4 1051.07
   425.9 1049.51   435.6 1048.72   455.0 1044.44   468.3 1043.30   474.3 1043.14
   483.3 1043.28   551.8 1047.58   600.2 1049.34   629.3 1051.87   639.0 1053.65
   677.7 1063.87   697.1 1065.88   706.8 1068.82   716.4 1075.35   745.5 1090.68
   755.2 1093.94   803.6 1104.15   832.7 1111.92   861.7 1121.73   910.1 1134.08
#Mann= 3 , 0 , 0
       0     0.1       0   468.3   0.045       0   483.3     0.1       0
Bank Sta=   468.3,   483.3
Exp/Cntr=0.3,0.1

Type RM Length L Ch R = 1 ,15899.8,362.485,362.448,362.4
XS GIS Cut Line= 3
     1747704.461      384026.703     1747273.827      384173.603
     1746843.193      384320.503
#Sta/Elev= 30
       0 1139.79     9.7 1136.57    19.4 1135.04    87.1 1114.33   106.5 1105.15
   174.3 1091.00   203.3 1083.14   280.7 1065.96   329.1 1052.79   387.2 1045.21
   437.5 1043.52   445.3 1043.49   452.5 1044.07   542.1 1046.28   561.5 1047.40
   580.9 1050.32   619.6 1062.19   638.9 1065.31   648.6 1068.89   668.0 1078.38
   677.7 1084.69   697.0 1090.97   716.4 1099.92   726.1 1102.08   774.5 1119.17
   793.8 1123.55   813.2 1129.95   822.9 1131.35   842.2 1138.10   910.0 1155.27
#Mann= 3 , 0 , 0
       0     0.1       0   437.5   0.045       0   452.5     0.1       0
Bank Sta=   437.5,   452.5
Exp/Cntr=0.3,0.1

Type RM Length L Ch R = 1 ,15537.3,796.199,800,807.777
XS GIS Cut Line= 3
     1747596.820      383679.664     1747166.433      383827.282
     1746736.112      383975.100
#Sta/Elev= 30
       0 1150.19    29.0 1138.75    67.8 1129.73    96.8 1120.97   106.5 1119.78
   135.5 1112.24   154.9 1105.53   164.6 1103.62   203.3 1092.20   251.7 1075.90
   261.4 1074.52   280.7 1066.88   309.8 1058.34   348.5 1051.49   416.3 1044.67
   447.5 1043.06   455.0 1043.03   462.5 1043.31   551.8 1045.06   580.9 1049.70
   619.6 1062.10   629.3 1064.40   648.6 1066.60   697.0 1087.14   735.7 1096.58
   774.5 1104.45   793.8 1109.82   803.5 1111.25   822.9 1117.06   910.0 1132.65
#Mann= 3 , 0 , 0
       0     0.1       0   447.5   0.045       0   462.5     0.1       0
Bank Sta=   447.5,   462.5
Exp/Cntr=0.3,0.1

Type RM Length L Ch R = 1 ,14737.3,401.263,400,399.601
XS GIS Cut Line= 3
     1747616.197      382985.773     1747171.352      383057.307
     1746692.406      383050.540
#Sta/Elev= 30
       0 1136.87    39.2 1133.06    68.6 1127.96    88.2 1124.26   156.7 1108.14
   176.3 1101.21   215.5 1090.52   235.1 1083.14   264.5 1074.62   333.0 1057.42
   362.4 1051.26   391.8 1046.55   421.2 1042.92   443.1 1041.82   450.6 1041.73
   458.1 1041.80   528.8 1044.13   587.4 1048.78   607.0 1051.48   646.1 1053.52
   665.6 1058.45   704.7 1063.26   734.0 1068.06   753.6 1072.68   782.9 1078.07
   792.7 1078.95   851.4 1090.63   880.7 1104.30   900.2 1110.45   929.6 1117.06
#Mann= 3 , 0 , 0
       0     0.1       0   443.1   0.045       0   458.1     0.1       0
Bank Sta=   443.1,   458.1
Exp/Cntr=0.3,0.1

Type RM Length L Ch R = 1 ,14337.3,399.405,400,392.4
XS GIS Cut Line= 3
     1747520.645      382585.404     1747055.109      382684.819
     1746604.697      382685.937
#Sta/Elev= 30
       0 1141.04    19.4 1133.72    68.0 1118.40    87.4 1110.85    97.1 1108.75
   116.6 1101.24   126.3 1099.46   145.7 1091.88   155.4 1090.02   174.9 1083.49
   184.6 1082.37   233.2 1067.40   272.0 1057.98   291.4 1055.61   408.0 1047.26
   466.3 1040.42   468.5 1040.64   476.0 1041.38   483.5 1045.27   525.0 1056.71
   544.6 1066.90   613.1 1082.21   642.5 1092.14   701.2 1107.06   769.8 1128.78
   789.4 1136.47   828.5 1146.82   848.1 1154.06   857.9 1155.99   926.4 1176.99
#Mann= 3 , 0 , 0
       0     0.1       0   468.5   0.045       0   483.5     0.1       0
Bank Sta=   468.5,   483.5
Exp/Cntr=0.3,0.1

Type RM Length L Ch R = 1 ,13937.3,405.862,400,393.926
XS GIS Cut Line= 3
     1747497.050      382200.343     1747054.511      382285.683
     1746602.386      382445.100
#Sta/Elev= 30
       0 1143.85     9.8 1142.39    29.4 1136.55    39.2 1135.32    58.8 1128.95
    98.0 1119.13   127.4 1109.67   166.6 1100.05   186.2 1093.27   215.5 1086.26
   362.5 1063.31   382.1 1058.87   401.7 1051.49   411.5 1049.77   431.1 1041.24
   443.2 1040.18   450.7 1040.17   458.2 1041.30   548.5 1046.33   577.9 1050.04
   646.4 1063.04   724.6 1084.88   734.4 1086.65   763.8 1095.07   783.3 1102.09
   793.1 1103.73   851.8 1122.97   891.0 1132.33   910.5 1139.10   930.1 1144.08
#Mann= 3 , 0 , 0
       0     0.1       0   443.2   0.045       0   458.2     0.1       0
Bank Sta=   443.2,   458.2
Exp/Cntr=0.3,0.1

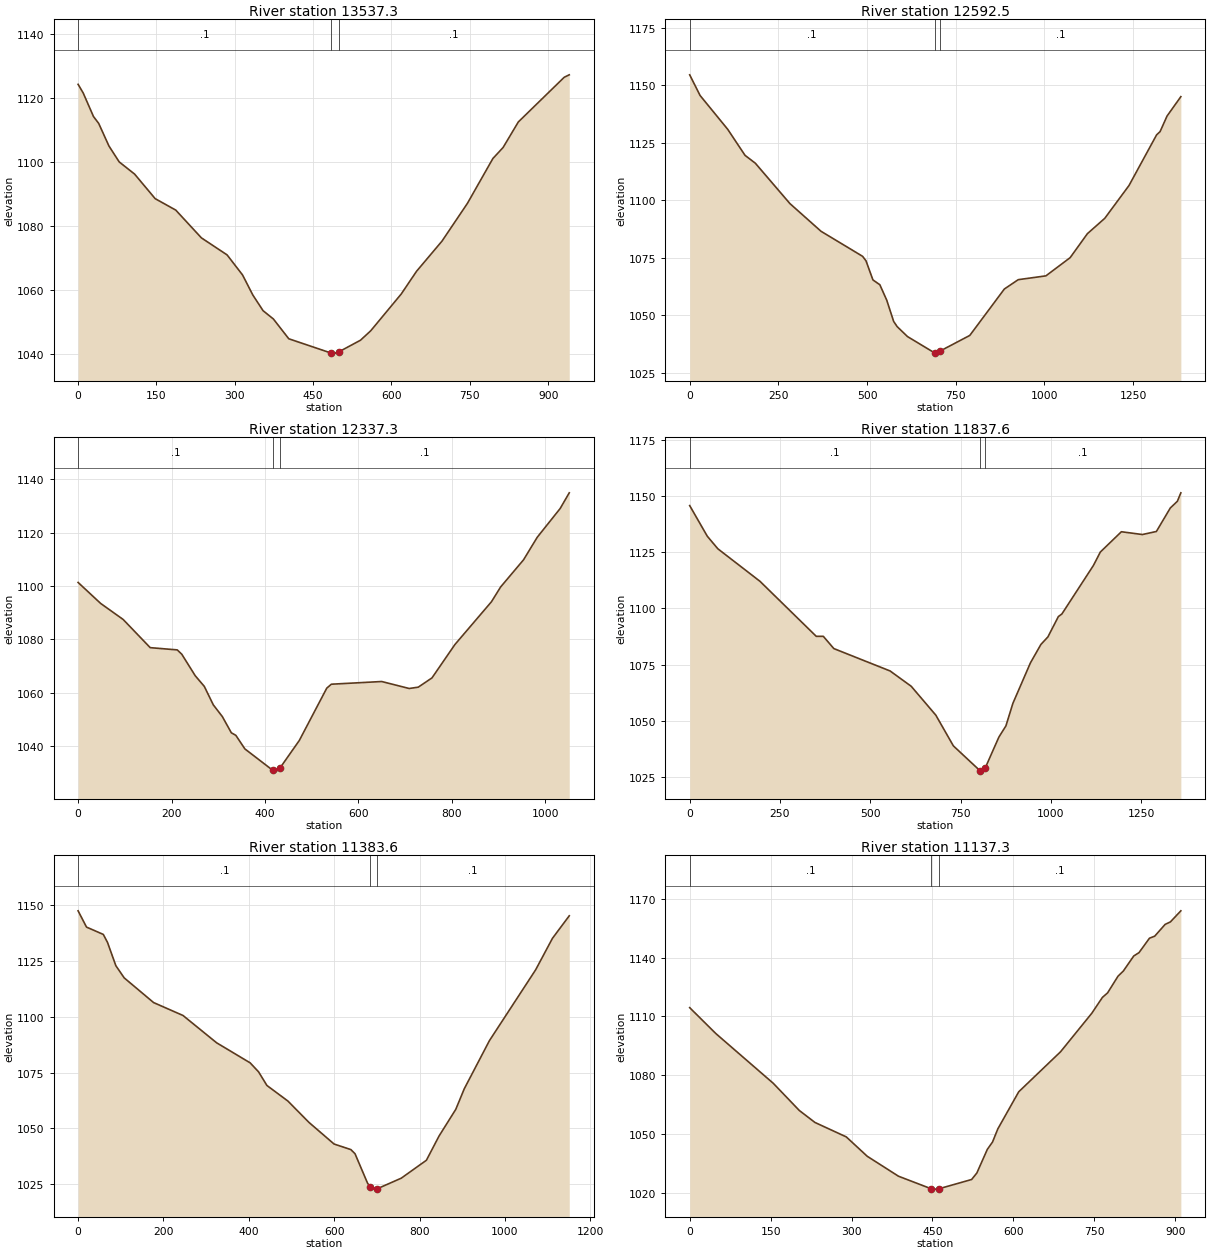
Type RM Length L Ch R = 1 ,13537.3,942.463,944.781,950.751
XS GIS Cut Line= 3
     1747248.233      381767.261     1746806.173      381983.191
     1746438.971      382240.620
#Sta/Elev= 30
       0 1124.20     9.8 1121.48    29.5 1114.13    39.4 1112.01    59.0 1104.96
    78.7 1099.97   108.2 1096.17   147.6 1088.50   187.0 1084.93   236.1 1076.26
   285.3 1070.94   314.9 1064.68   334.5 1058.44   354.2 1053.52   373.9 1050.94
   403.4 1044.76   484.5 1040.30   492.0 1040.28   499.5 1040.70   540.7 1044.31
   560.2 1047.24   618.7 1058.74   648.0 1065.83   696.7 1075.24   745.4 1087.03
   794.2 1101.04   813.7 1104.47   842.9 1112.45   930.7 1126.39   940.4 1127.16
#Mann= 3 , 0 , 0
       0     0.1       0   484.5   0.045       0   499.5     0.1       0
Bank Sta=   484.5,   499.5
Exp/Cntr=0.3,0.1

Type RM Length L Ch R = 1 ,12592.5,259.429,255.219,252.45
XS GIS Cut Line= 3
     1747446.934      381035.085     1746811.190      381282.917
     1746153.897      381530.749
#Sta/Elev= 30
       0 1154.58    29.2 1145.61   107.2 1130.87   156.0 1119.55   185.2 1116.10
   282.7 1098.54   370.4 1086.49   487.4 1075.62   497.1 1073.65   516.6 1065.35
   536.1 1063.25   555.6 1056.51   575.1 1047.27   584.9 1045.03   614.1 1040.69
   690.7 1033.57   692.1 1033.49   705.7 1034.37   789.7 1041.19   887.2 1061.39
   926.3 1065.45  1004.3 1067.11  1072.6 1075.02  1121.4 1085.48  1170.2 1092.13
  1238.5 1106.40  1316.5 1128.48  1326.3 1129.89  1345.8 1136.63  1384.8 1145.08
#Mann= 3 , 0 , 0
       0     0.1       0   690.7   0.045       0   705.7     0.1       0
Bank Sta=   690.7,   705.7
Exp/Cntr=0.3,0.1

Type RM Length L Ch R = 1 ,12337.3,503.298,499.703,494.463
XS GIS Cut Line= 3
     1747037.181      380841.966     1746675.307      381064.170
     1746120.171      381355.606
#Sta/Elev= 30
       0 1101.34    48.3 1093.47    96.5 1087.46   154.4 1076.90   212.3 1076.06
   222.0 1074.44   250.9 1066.35   270.2 1062.39   289.5 1055.46   308.8 1051.08
   328.1 1045.00   337.8 1044.03   357.1 1038.96   417.1 1030.90   424.6 1030.63
   432.1 1031.76   473.6 1042.11   532.4 1061.72   542.2 1063.20   650.0 1064.21
   708.8 1061.60   728.3 1062.09   757.7 1065.57   806.7 1078.05   885.1 1094.12
   904.7 1099.65   953.7 1109.81   983.1 1118.28  1032.0 1129.01  1051.6 1134.92
#Mann= 3 , 0 , 0
       0     0.1       0   417.1   0.045       0   432.1     0.1       0
Bank Sta=   417.1,   432.1
Exp/Cntr=0.3,0.1

Type RM Length L Ch R = 1 ,11837.6,439.137,453.999,468.99
XS GIS Cut Line= 3
     1746978.208      380512.483     1746321.998      380875.045
     1745862.963      381277.530
#Sta/Elev= 30
       0 1145.65    48.7 1132.06    77.9 1126.48   194.7 1112.02   350.5 1087.59
   370.0 1087.60   399.2 1082.15   555.0 1072.21   613.4 1065.42   681.6 1052.59
   730.2 1038.95   803.4 1028.00   807.9 1027.73   818.4 1029.11   856.3 1042.86
   875.7 1047.81   895.1 1057.85   943.5 1075.77   972.6 1083.98   992.0 1087.33
  1021.0 1096.37  1030.7 1097.52  1117.9 1119.02  1137.3 1125.04  1195.5 1134.04
  1253.6 1132.80  1292.4 1134.15  1331.1 1144.61  1350.5 1147.56  1360.2 1151.32
#Mann= 3 , 0 , 0
       0     0.1       0   803.4   0.045       0   818.4     0.1       0
Bank Sta=   803.4,   818.4
Exp/Cntr=0.3,0.1

Type RM Length L Ch R = 1 ,11383.6,249.301,246.298,244.021
XS GIS Cut Line= 3
     1746956.657      380447.831     1746240.099      380485.545
     1745811.050      380543.376
#Sta/Elev= 30
       0 1147.56    19.7 1140.27    59.0 1136.98    68.8 1133.44    88.5 1122.94
   108.1 1117.48   176.9 1106.42   245.7 1100.64   324.4 1088.40   403.0 1079.40
   422.7 1075.38   442.3 1069.26   491.5 1062.26   540.6 1052.73   599.6 1043.00
   638.9 1040.51   648.7 1038.64   678.2 1025.37   684.7 1023.85   697.9 1022.78
   699.7 1022.86   756.9 1027.68   815.9 1035.73   845.5 1046.59   884.8 1058.59
   904.5 1067.74   963.5 1089.35  1071.8 1121.12  1111.1 1135.22  1150.5 1145.33
#Mann= 3 , 0 , 0
       0     0.1       0   684.7   0.045       0   699.7     0.1       0
Bank Sta=   684.7,   699.7
Exp/Cntr=0.3,0.1

Type RM Length L Ch R = 1 ,11137.3,403.971,400,396.957
XS GIS Cut Line= 3
     1746712.365      380155.421     1746265.290      380239.319
     1745814.944      380308.877
#Sta/Elev= 30
       0 1114.48    48.4 1101.31   154.9 1075.98   203.2 1062.14   232.3 1056.02
   290.3 1048.69   329.1 1038.83   387.1 1028.66   447.4 1022.31   454.9 1022.09
   462.4 1022.30   522.7 1026.99   532.4 1030.31   551.8 1042.33   561.5 1046.09
   571.2 1052.72   610.0 1071.64   687.6 1092.03   745.7 1111.71   765.1 1119.67
   774.8 1122.02   794.2 1130.54   803.9 1133.11   823.3 1140.80   833.0 1142.48
   852.4 1149.84   862.1 1150.87   881.5 1156.89   891.2 1158.14   910.6 1163.78
#Mann= 3 , 0 , 0
       0     0.1       0   447.4   0.045       0   462.4     0.1       0
Bank Sta=   447.4,   462.4
Exp/Cntr=0.3,0.1