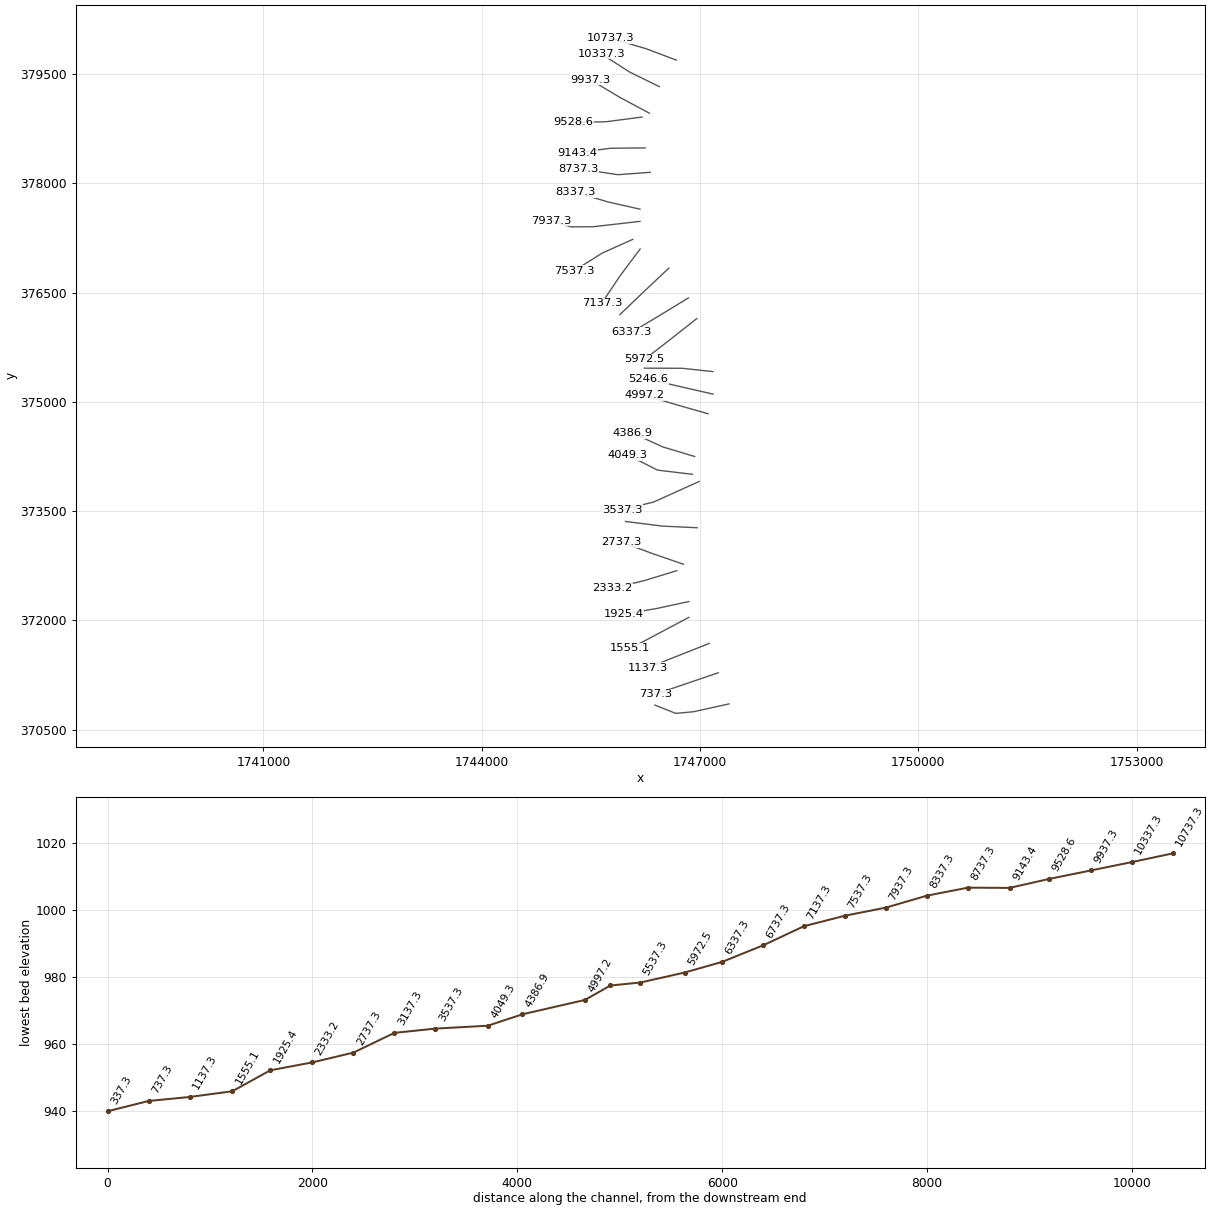
HEC-RAS study PlmRn.prj: PlmRn

--- PlmRn.g01 (geometry) --- (continued)

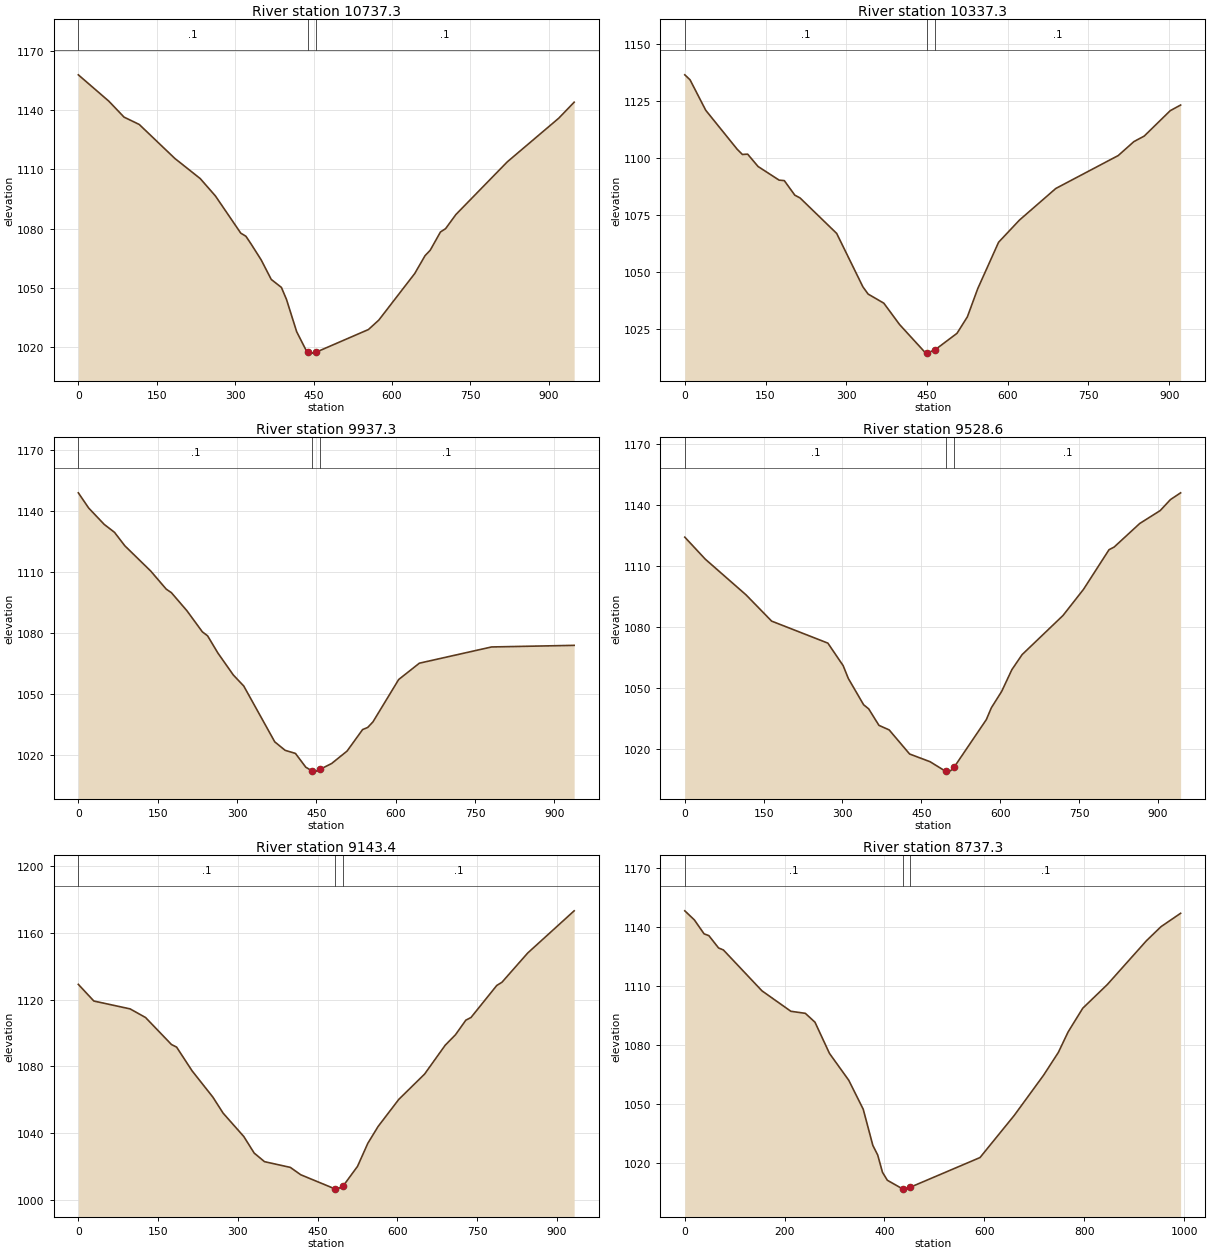
Type RM Length L Ch R = 1 ,10737.3,402.097,400,393.661
XS GIS Cut Line= 3
     1746674.786      379693.610     1746256.720      379850.959
     1745775.570      379992.699
#Sta/Elev= 30
       0 1157.74    58.3 1144.43    87.4 1136.36   116.5 1132.64   184.5 1115.48
   233.1 1105.28   262.2 1096.49   310.7 1077.68   320.5 1076.11   330.2 1072.29
   349.6 1064.21   369.0 1054.27   388.4 1050.23   398.1 1044.18   417.6 1027.84
   437.0 1017.76   439.2 1017.59   446.7 1017.01   454.2 1017.42   554.9 1028.95
   574.6 1033.69   643.4 1057.27   663.1 1066.28   672.9 1069.00   692.6 1078.27
   702.4 1079.95   722.1 1087.09   820.4 1113.73   918.8 1135.80   948.3 1143.90
#Mann= 3 , 0 , 0
       0     0.1       0   439.2   0.045       0   454.2     0.1       0
Bank Sta=   439.2,   454.2
Exp/Cntr=0.3,0.1

Type RM Length L Ch R = 1 ,10337.3,400.754,400,400.771
XS GIS Cut Line= 3
     1746441.597      379329.324     1746030.916      379530.653
     1745640.499      379781.138
#Sta/Elev= 30
       0 1136.29     9.7 1134.13    38.9 1120.77    97.3 1103.71   107.0 1101.41
   116.8 1101.55   136.2 1096.13   175.2 1090.18   184.9 1089.95   204.4 1083.59
   214.1 1082.38   282.2 1066.83   330.9 1043.44   340.6 1040.28   369.8 1036.28
   399.0 1026.94   447.6 1014.41   449.9 1014.43   464.9 1015.85   505.7 1023.08
   525.0 1030.30   544.3 1042.67   583.0 1062.97   621.7 1072.66   689.3 1086.52
   805.3 1100.94   834.3 1107.03   853.6 1109.47   901.9 1120.59   921.2 1123.06
#Mann= 3 , 0 , 0
       0     0.1       0   449.9   0.045       0   464.9     0.1       0
Bank Sta=   449.9,   464.9
Exp/Cntr=0.3,0.1

Type RM Length L Ch R = 1 ,9937.3,395.379,408.695,421.465
XS GIS Cut Line= 3
     1746305.523      378964.054     1745909.105      379175.944
     1745490.290      379425.771
#Sta/Elev= 30
       0 1148.87    19.5 1141.41    48.9 1133.34    68.4 1129.42    87.9 1122.80
   136.8 1110.38   166.1 1101.48   175.9 1099.73   205.2 1090.86   234.5 1080.43
   244.3 1078.51   263.8 1070.02   293.1 1059.17   312.7 1053.78   371.3 1026.30
   390.9 1022.14   410.4 1020.61   430.0 1013.82     442 1011.96   449.5 1011.90
     457 1012.79   478.8 1015.65   508.0 1021.78   537.3 1032.35   547.0 1033.40
   556.8 1036.10   605.5 1056.98   644.6 1065.02   781.1 1073.01   937.2 1073.80
#Mann= 3 , 0 , 0
       0     0.1       0     442   0.045       0     457     0.1       0
Bank Sta=     442,     457
Exp/Cntr=0.3,0.1

Type RM Length L Ch R = 1 ,9528.6,388.738,385.201,386.381
XS GIS Cut Line= 3
     1746202.554      378911.615     1745710.974      378847.541
     1745263.481      378837.863
#Sta/Elev= 30
       0 1124.40    38.9 1113.60   116.6 1096.01   165.2 1083.12   272.2 1072.30
   301.3 1061.21   311.1 1054.93   340.2 1042.00   349.9 1039.96   369.4 1031.86
   388.8 1029.63   427.7 1017.78   466.6 1013.99   495.7 1009.36   497.8 1009.39
   505.5 1009.50   512.8 1011.46   573.6 1034.67   583.3 1040.54   602.8 1048.54
   622.2 1059.23   641.7 1066.64   719.5 1085.88   758.5 1098.73   807.1 1118.23
   816.8 1119.53   865.5 1131.12   904.4 1137.46   923.9 1142.87   943.3 1146.20
#Mann= 3 , 0 , 0
       0     0.1       0   497.8   0.045       0   512.8     0.1       0
Bank Sta=   497.8,   512.8
Exp/Cntr=0.3,0.1

Type RM Length L Ch R = 1 ,9143.4,402.626,406.104,400.983
XS GIS Cut Line= 3
     1746246.218      378488.190     1745769.693      378483.296
     1745317.794      378423.436
#Sta/Elev= 30
       0 1129.10    29.2 1119.13    97.3 1114.44   126.4 1109.28   175.1 1093.15
   184.8 1091.58   214.0 1077.37   252.9 1061.73   272.3 1052.10   311.2 1038.12
   330.7 1028.23   350.1 1023.10   398.7 1019.67   418.2 1015.28   482.3 1006.86
   486.2 1006.68   497.3 1008.26   525.0 1020.29   544.4 1034.08   563.8 1044.17
   602.6 1060.32   651.1 1075.45   689.9 1092.71   709.3 1099.00   728.7 1107.69
   738.4 1109.29   786.9 1128.45   796.6 1130.35   845.1 1147.85   932.4 1173.06
#Mann= 3 , 0 , 0
       0     0.1       0   482.3   0.045       0   497.3     0.1       0
Bank Sta=   482.3,   497.3
Exp/Cntr=0.3,0.1

Type RM Length L Ch R = 1 ,8737.3,407.229,400,396.712
XS GIS Cut Line= 3
     1746315.526      378152.690     1745872.384      378120.102
     1745329.586      378201.179
#Sta/Elev= 30
       0 1148.31    19.3 1143.66    38.6 1136.61    48.3 1135.67    67.6 1129.43
    77.3 1128.41   154.6 1107.61   212.5 1097.21   241.5 1096.17   260.8 1091.65
   289.8 1075.79   328.4 1062.14   357.4 1047.41   376.7 1028.98   386.4 1024.11
   396.0 1015.31   405.7 1011.27   436.8 1006.78   444.3 1006.75   451.8 1007.73
   591.3 1022.80   659.9 1044.24   718.7 1064.70   748.2 1076.26   767.8 1086.69
   797.2 1098.78   846.2 1110.77   924.6 1133.07   954.0 1140.27   993.2 1147.06
#Mann= 3 , 0 , 0
       0     0.1       0   436.8   0.045       0   451.8     0.1       0
Bank Sta=   436.8,   451.8
Exp/Cntr=0.3,0.1

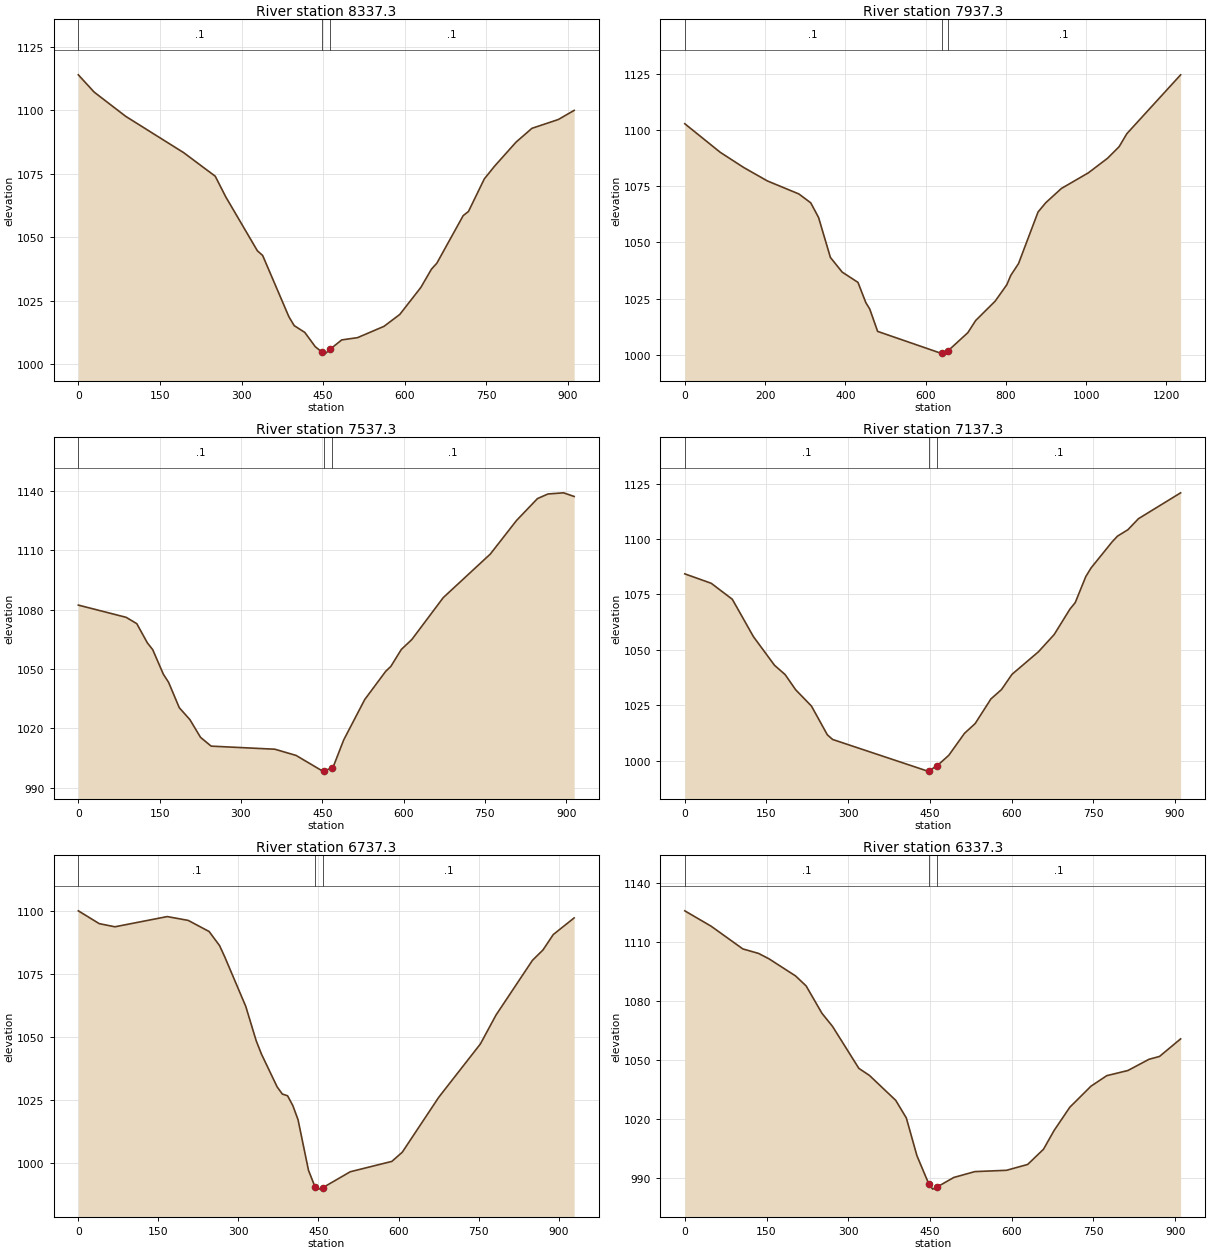
Type RM Length L Ch R = 1 ,8337.3,391.886,400,406.899
XS GIS Cut Line= 3
     1746175.273      377646.724     1745731.684      377746.941
     1745294.555      377877.849
#Sta/Elev= 30
       0 1114.06    29.0 1107.27    87.1 1097.69   193.5 1083.39   251.6 1074.09
   270.9 1065.96   329.0 1044.71   338.7 1042.86   387.0 1018.67   396.7 1015.19
   416.1 1012.54   435.4 1006.89   447.3 1004.84   454.8 1004.36   462.3 1005.83
   483.9 1009.56   513.0 1010.46   561.6 1014.91   590.7 1019.61   629.5 1030.29
   648.9 1037.47   658.7 1039.78   707.2 1058.56   716.9 1060.20   746.0 1073.04
   765.4 1078.19   804.3 1087.52   833.4 1092.96   882.0 1096.44   911.1 1100.05
#Mann= 3 , 0 , 0
       0     0.1       0   447.3   0.045       0   462.3     0.1       0
Bank Sta=   447.3,   462.3
Exp/Cntr=0.3,0.1

Type RM Length L Ch R = 1 ,7937.3,393.572,400,412.379
XS GIS Cut Line= 4
     1746175.447      377479.234     1745532.471      377405.630
     1745221.833      377403.807     1744957.838      377490.009
#Sta/Elev= 30
       0 1102.73    88.3 1090.04   147.1 1083.25   205.9 1077.30   284.4 1071.51
   313.8 1067.59   333.4 1061.04   362.8 1043.32   392.2 1036.79   431.5 1032.23
   451.1 1023.24   460.9 1020.37   480.5 1010.44   637.4 1000.78   639.7 1000.78
   654.7 1001.60   705.4 1009.89   724.8 1015.28   773.4 1023.89   802.5 1031.20
   812.2 1035.31   831.6 1040.58   880.2 1063.49   899.6 1067.65   938.4 1073.96
  1005.7 1080.92  1053.6 1087.41  1082.3 1092.54  1101.5 1098.31  1235.5 1124.47
#Mann= 3 , 0 , 0
       0     0.1       0   639.7   0.045       0   654.7     0.1       0
Bank Sta=   639.7,   654.7
Exp/Cntr=0.3,0.1

Type RM Length L Ch R = 1 ,7537.3,388.572,400,409.408
XS GIS Cut Line= 3
     1746075.988      377231.960     1745655.778      377043.496
     1745271.655      376801.449
#Sta/Elev= 30
       0 1082.25    88.2 1076.07   107.8 1072.88   127.4 1063.14   137.2 1059.74
   156.8 1047.35   166.6 1043.17   186.2 1030.40   205.8 1024.38   225.4 1015.42
   245.0 1010.98   362.6 1009.42   401.7 1006.28   450.7  998.35     453  998.39
     468 1000.08   470.2 1000.54   489.5 1014.11   528.2 1034.48   566.8 1048.73
   576.5 1051.29   595.8 1059.84   615.1 1064.83   673.1 1086.01   760.0 1108.06
   808.3 1125.01   846.9 1136.06   866.3 1138.40   895.2 1138.98   914.6 1137.13
#Mann= 3 , 0 , 0
       0     0.1       0     453   0.045       0     468     0.1       0
Bank Sta=     453,     468
Exp/Cntr=0.3,0.1

Type RM Length L Ch R = 1 ,7137.3,403.914,400,395.09
XS GIS Cut Line= 3
     1746177.269      377099.386     1745903.987      376734.670
     1745650.444      376357.017
#Sta/Elev= 30
       0 1084.27    48.5 1080.02    87.3 1072.79   126.1 1055.91   164.8 1042.99
   184.2 1038.83   203.6 1031.96   232.7 1024.56   261.8 1011.61   271.5 1009.51
   446.0  995.22   448.2  995.38   463.2  997.61   484.8 1002.35   513.8 1012.32
   533.2 1016.67   562.2 1027.81   581.6 1032.02   600.9 1038.92   649.3 1049.05
   678.3 1056.85   707.4 1068.39   717.0 1071.27   736.4 1083.02   746.1 1086.94
   784.8 1098.71   794.5 1101.27   813.8 1104.20   833.2 1109.18   910.6 1120.85
#Mann= 3 , 0 , 0
       0     0.1       0   448.2   0.045       0   463.2     0.1       0
Bank Sta=   448.2,   463.2
Exp/Cntr=0.3,0.1

Type RM Length L Ch R = 1 ,6737.3,404.711,400,394.978
XS GIS Cut Line= 3
     1746572.649      376838.079     1746244.473      376528.850
     1745898.965      376198.301
#Sta/Elev= 30
       0 1100.17    39.2 1095.07    68.6 1093.82   166.6 1097.88   205.9 1096.36
   245.1 1091.94   264.7 1086.32   274.5 1081.79   313.7 1062.19   333.3 1048.49
   343.1 1043.21   372.5 1030.16   382.3 1027.28   392.1 1026.61   401.9 1022.72
   411.7 1017.09   431.3  996.96   443.4  990.44   450.9  989.47   458.4  990.08
   509.5  996.38   587.5 1000.50   607.0 1004.15   675.4 1026.02   753.4 1047.22
   782.7 1058.73   851.0 1080.49   870.5 1084.56   890.0 1090.74   929.1 1097.35
#Mann= 3 , 0 , 0
       0     0.1       0   443.4   0.045       0   458.4     0.1       0
Bank Sta=   443.4,   458.4
Exp/Cntr=0.3,0.1

Type RM Length L Ch R = 1 ,6337.3,362.045,364.757,367.561
XS GIS Cut Line= 3
     1746840.109      376427.357     1746451.543      376190.628
     1746061.503      375956.314
#Sta/Elev= 30
       0 1126.01    48.4 1118.18   106.5 1106.65   135.5 1104.34   154.9 1101.55
   203.3 1092.91   222.7 1087.83   251.7 1073.93   271.1 1067.27   319.5 1045.90
   338.8 1042.35   387.2 1029.64   406.6 1020.70   426.0 1001.55   447.5  987.37
   455.0  984.52   462.5  985.53   493.7  990.45   532.4  993.43   590.5  994.09
   629.3  997.07   658.3 1004.78   677.7 1014.30   706.7 1026.18   745.4 1036.84
   774.5 1042.21   813.2 1044.82   851.9 1050.52   871.3 1051.99   910.0 1060.91
#Mann= 3 , 0 , 0
       0     0.1       0   447.5   0.045       0   462.5     0.1       0
Bank Sta=   447.5,   462.5
Exp/Cntr=0.3,0.1

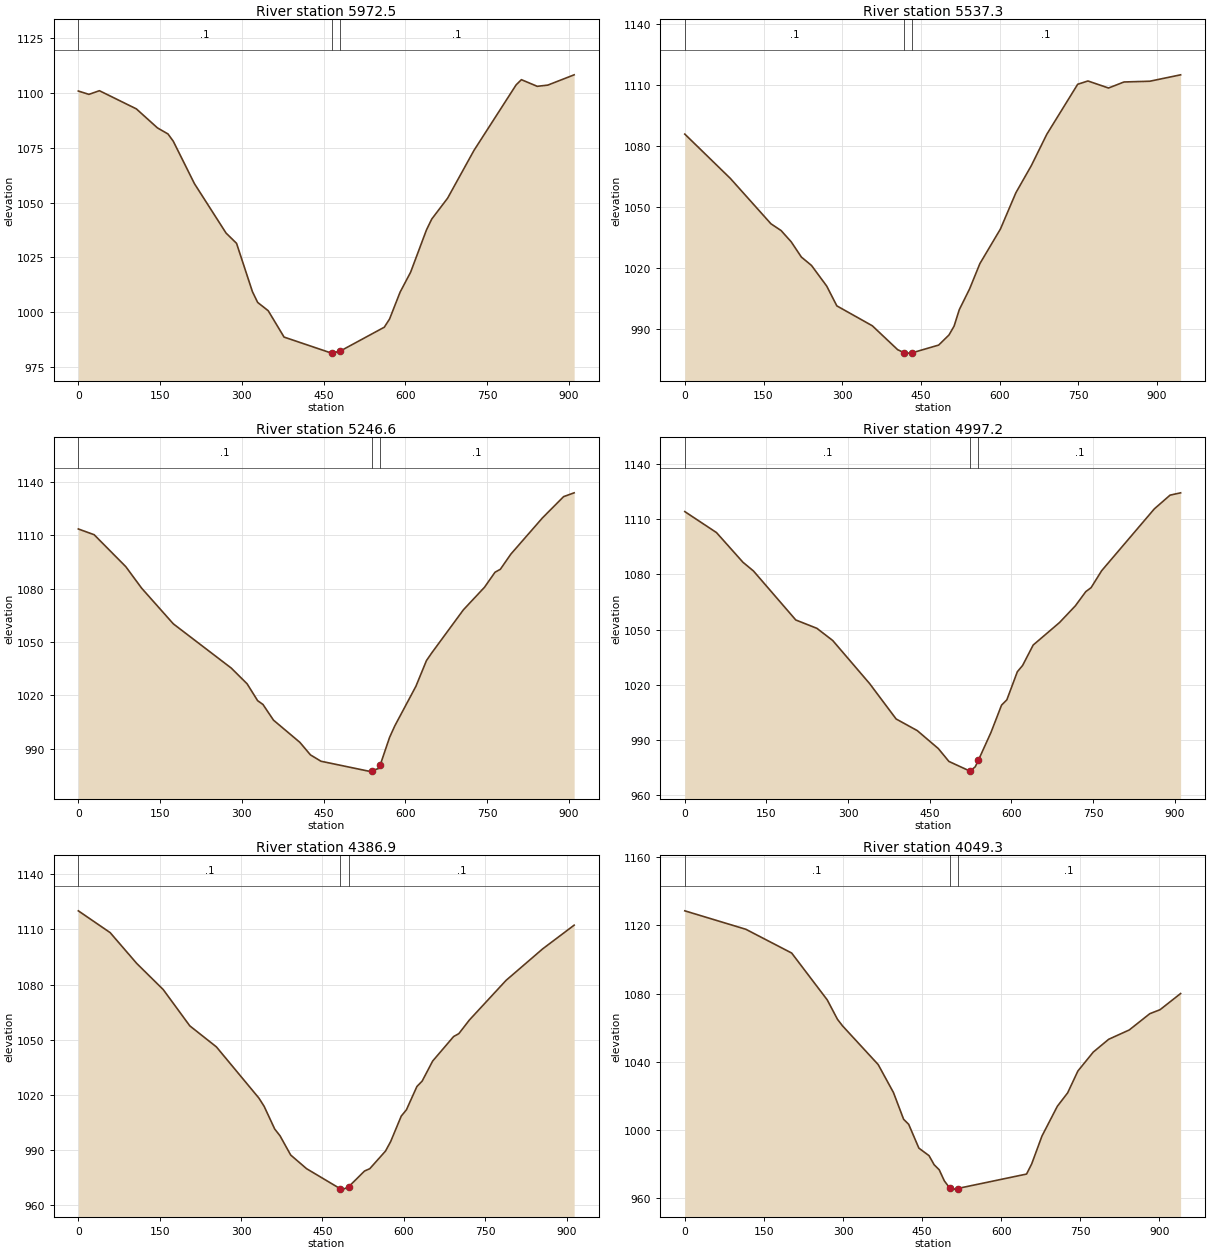
Type RM Length L Ch R = 1 ,5972.5,453.099,435.243,418.12
XS GIS Cut Line= 3
     1746956.465      376144.647     1746599.098      375863.024
     1746239.422      375584.323
#Sta/Elev= 30
       0 1100.82    19.4 1099.30    38.7 1100.97   106.5 1092.69   145.2 1084.02
   164.6 1081.24   174.3 1077.92   213.0 1058.64   271.1 1036.08   290.4 1031.38
   319.5 1009.38   329.1 1004.46   348.5 1000.67   377.6  988.65   464.7  981.34
   465.1  981.35   480.1  982.20   561.5  993.15   571.2  996.88   590.5 1009.11
   609.9 1018.26   638.9 1037.48   648.6 1042.45   677.7 1051.96   726.1 1073.74
   803.5 1103.63   813.2 1106.00   842.2 1102.97   861.6 1103.52   910.0 1108.21
#Mann= 3 , 0 , 0
       0     0.1       0   465.1   0.045       0   480.1     0.1       0
Bank Sta=   465.1,   480.1
Exp/Cntr=0.3,0.1

Type RM Length L Ch R = 1 ,5537.3,293.913,290.718,286.388
XS GIS Cut Line= 3
     1747177.551      375415.763     1746755.027      375461.629
     1746235.066      375462.966
#Sta/Elev= 30
       0 1085.88    86.9 1064.10   164.2 1041.84   183.5 1038.53   202.8 1032.99
   222.2 1025.50   241.5 1021.38   270.5 1011.24   289.8 1001.53   357.4  991.76
   405.7  980.02   417.5  978.58   425.0  978.33   432.5  978.42   483.9  982.29
   503.5  987.24   513.3  991.61   523.1  999.64   542.7 1009.82   562.4 1022.28
   601.6 1039.29   631.0 1057.07   660.5 1070.43   689.9 1085.77   748.8 1110.35
   768.4 1111.97   807.6 1108.51   837.1 1111.48   886.1 1111.84   945.0 1114.99
#Mann= 3 , 0 , 0
       0     0.1       0   417.5   0.045       0   432.5     0.1       0
Bank Sta=   417.5,   432.5
Exp/Cntr=0.3,0.1

Type RM Length L Ch R = 1 ,5246.6,250.956,249.368,247.78
XS GIS Cut Line= 3
     1747179.792      375106.721     1746736.257      375208.217
     1746292.722      375309.714
#Sta/Elev= 30
       0 1113.51    29.0 1110.29    87.1 1092.34   116.2 1080.24   174.3 1060.21
   280.7 1035.34   309.8 1026.50   329.1 1017.03   338.8 1014.93   358.2 1006.09
   406.6  993.62   426.0  986.58   445.3  983.01   532.4  977.45   539.1  977.75
   551.8  979.00   554.1  980.95   571.2  996.37   580.9 1002.93   619.6 1025.14
   638.9 1039.55   648.6 1043.86   706.7 1068.08   745.4 1080.74   764.8 1089.22
   774.5 1090.85   793.8 1099.37   851.9 1119.76   890.6 1131.68   910.0 1133.82
#Mann= 3 , 0 , 0
       0     0.1       0   539.1   0.045       0   554.1     0.1       0
Bank Sta=   539.1,   554.1
Exp/Cntr=0.3,0.1

Type RM Length L Ch R = 1 ,4997.2,613.359,610.311,607.264
XS GIS Cut Line= 3
     1747110.305      374837.650     1746671.383      374962.157
     1746236.210      375094.165
#Sta/Elev= 30
       0 1114.13    58.2 1102.74   106.8 1086.62   126.2 1081.86   203.9 1055.25
   242.7 1050.71   271.8 1044.09   339.8 1020.60   388.3 1001.45   427.1  995.14
   465.9  985.35   485.3  978.38   524.0  973.12   524.4  973.21   533.6  975.47
   539.4  979.03   562.7  994.25   582.0 1008.99   591.7 1011.85   611.0 1027.12
   620.7 1030.54   640.1 1041.63   688.5 1053.85   717.5 1062.90   736.8 1070.66
   746.5 1072.80   765.9 1082.01   862.6 1115.58   891.6 1123.07   911.0 1124.33
#Mann= 3 , 0 , 0
       0     0.1       0   524.4   0.045       0   539.4     0.1       0
Bank Sta=   524.4,   539.4
Exp/Cntr=0.3,0.1

Type RM Length L Ch R = 1 ,4386.9,338.545,337.641,336.737
XS GIS Cut Line= 3
     1746926.280      374250.309     1746485.697      374382.502
     1746072.953      374571.890
#Sta/Elev= 30
       0 1120.13    58.7 1108.27   107.7 1091.51   156.6 1077.29   205.5 1057.59
   254.5 1046.17   332.8 1018.36   342.5 1013.87   362.1 1001.47   371.9  997.79
   391.5  987.36   420.8  979.93   483.1  968.99   489.0  968.82   498.1  970.03
   527.6  978.65   537.3  979.93   566.3  989.51   575.9  994.73   595.3 1008.51
   604.9 1011.98   624.2 1024.62   633.9 1027.57   653.2 1038.44   691.9 1051.79
   701.5 1053.35   720.9 1060.75   788.5 1082.30   856.1 1099.46   914.1 1112.34
#Mann= 3 , 0 , 0
       0     0.1       0   483.1   0.045       0   498.1     0.1       0
Bank Sta=   483.1,   498.1
Exp/Cntr=0.3,0.1

Type RM Length L Ch R = 1 ,4049.3,491.866,511.962,527.458
XS GIS Cut Line= 3
     1746894.461      374005.821     1746415.350      374062.979
     1746007.369      374270.583
#Sta/Elev= 30
       0 1128.55   115.8 1117.73   202.7 1103.80   270.2 1076.31   289.5 1064.98
   299.2 1061.08   366.7 1038.44   395.7 1022.04   415.0 1006.34   424.6 1003.40
   443.9  989.44   463.2  985.01   472.9  979.68   482.5  976.73   492.2  970.24
   502.2  966.13   511.7  965.40   517.2  965.76   648.1  974.23   657.8  980.14
   677.3  996.49   706.5 1013.97   726.0 1021.81   745.5 1034.65   774.7 1045.76
   803.9 1053.25   842.9 1058.71   881.8 1068.24   901.3 1070.59   940.3 1080.07
#Mann= 3 , 0 , 0
       0     0.1       0   502.2   0.045       0   517.2     0.1       0
Bank Sta=   502.2,   517.2
Exp/Cntr=0.3,0.1

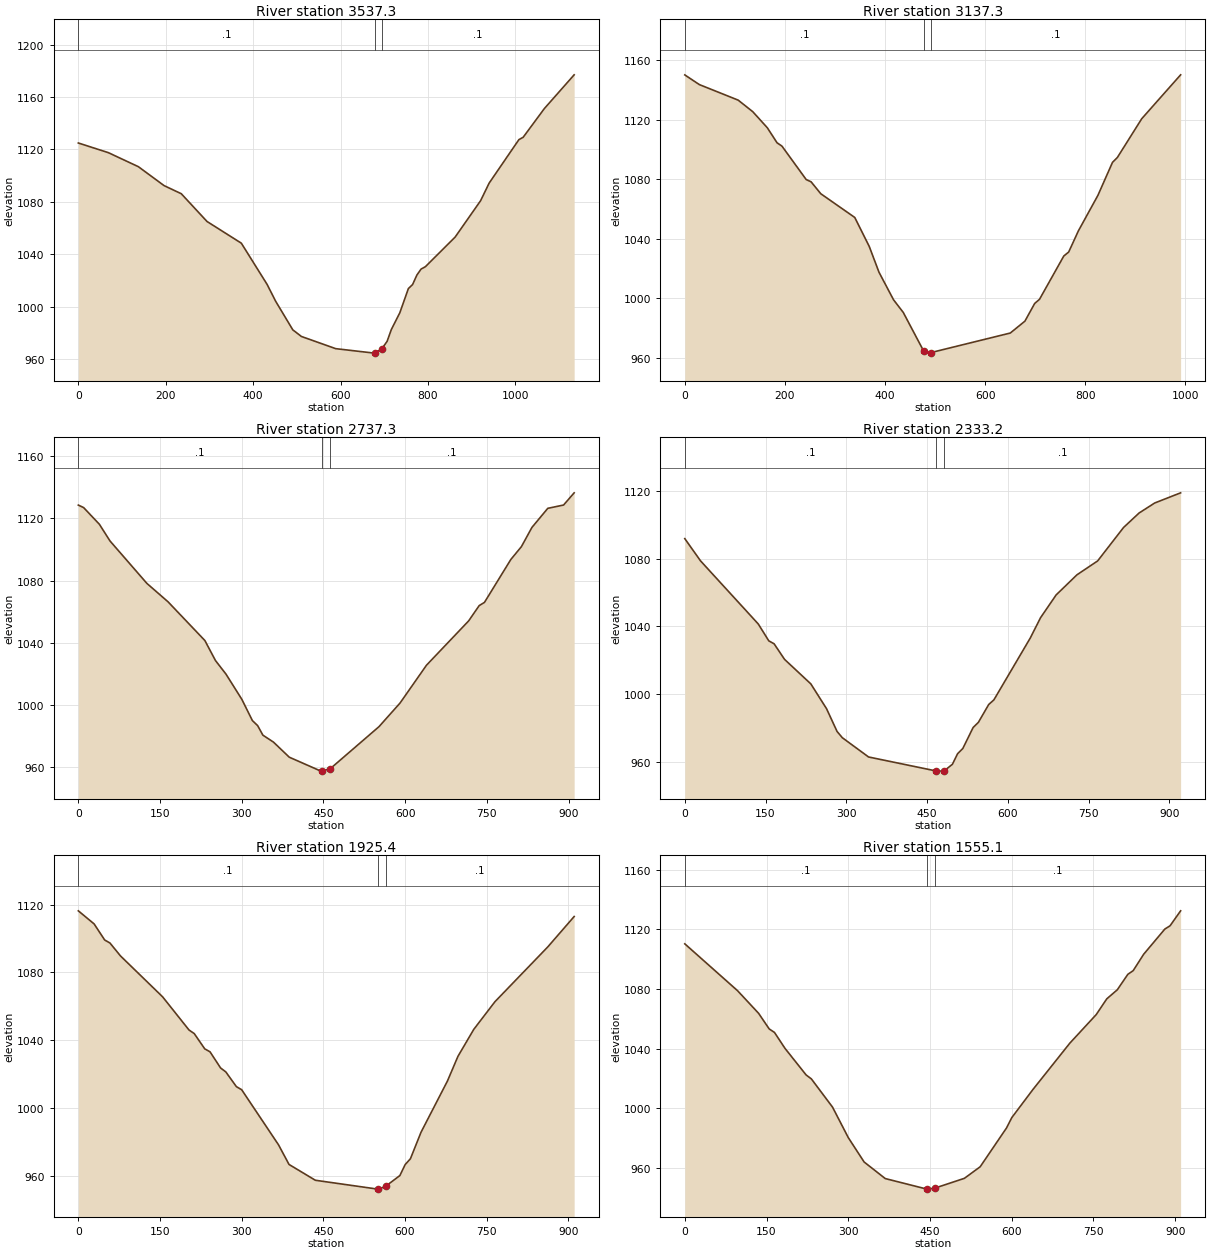
Type RM Length L Ch R = 1 ,3537.3,410.21,400,392.568
XS GIS Cut Line= 3
     1746988.983      373907.219     1746362.617      373624.678
     1745927.615      373519.308
#Sta/Elev= 30
       0 1124.90    68.7 1117.53   137.4 1106.82   196.3 1092.36   235.6 1086.19
   294.5 1065.00   373.0 1048.45   431.9 1017.06   451.6 1004.12   490.8  982.32
   510.4  977.27   589.0  967.95   677.3  964.54   679.6  964.71   694.6  967.88
   706.6  973.50   716.3  982.53   735.8  995.38   755.3 1013.79   765.0 1016.90
   774.7 1024.07   784.4 1028.69   794.2 1030.48   862.3 1053.09   920.7 1080.91
   940.1 1094.26  1008.2 1127.45  1018.0 1129.26  1066.6 1151.21  1134.7 1176.92
#Mann= 3 , 0 , 0
       0     0.1       0   679.6   0.045       0   694.6     0.1       0
Bank Sta=   679.6,   694.6
Exp/Cntr=0.3,0.1

Type RM Length L Ch R = 1 ,3137.3,406.521,400,394.809
XS GIS Cut Line= 3
     1746962.045      373271.476     1746477.668      373294.713
     1745976.104      373357.679
#Sta/Elev= 30
       0 1150.13    29.1 1143.62   106.7 1133.17   135.8 1125.41   164.9 1114.61
   184.3 1104.52   194.0 1102.32   242.5 1079.84   252.2 1078.35   271.6 1070.33
   339.5 1054.38   368.5 1034.87   387.9 1017.60   417.0  999.07   436.4  990.58
   477.4  964.49   484.9  963.26   492.4  963.68   650.2  976.76   679.4  984.74
   698.8  996.58   708.5  999.40   757.1 1028.51   766.8 1031.16   786.3 1045.44
   825.2 1069.23   854.3 1091.37   864.1 1094.68   912.7 1120.69   990.4 1150.18
#Mann= 3 , 0 , 0
       0     0.1       0   477.4   0.045       0   492.4     0.1       0
Bank Sta=   477.4,   492.4
Exp/Cntr=0.3,0.1

Type RM Length L Ch R = 1 ,2737.3,389.597,404.151,417.994
XS GIS Cut Line= 3
     1746773.906      372770.057     1746343.704      372918.145
     1745916.697      373075.658
#Sta/Elev= 30
       0 1128.56     9.7 1126.97    38.7 1116.20    58.1 1105.50   125.8 1078.19
   164.6 1066.34   232.3 1041.39   251.7 1028.53   271.0 1019.79   300.1 1003.57
   319.5  989.88   329.1  986.66   338.8  980.49   358.2  976.02   387.2  966.32
   445.3  957.35   447.5  957.40   462.5  958.94   551.8  985.94   590.5 1001.16
   639.0 1025.49   716.4 1054.02   735.8 1063.88   745.5 1065.96   793.9 1093.58
   813.3 1101.82   832.6 1114.19   861.7 1126.48   890.7 1128.61   910.1 1136.46
#Mann= 3 , 0 , 0
       0     0.1       0   447.5   0.045       0   462.5     0.1       0
Bank Sta=   447.5,   462.5
Exp/Cntr=0.3,0.1

Type RM Length L Ch R = 1 ,2333.2,410.924,407.789,405.857
XS GIS Cut Line= 3
     1746682.071      372682.110     1746234.290      372545.632
     1745794.082      372440.084
#Sta/Elev= 30
       0 1091.98    29.3 1078.80   136.5 1041.46   156.0 1031.49   165.8 1029.77
   185.3 1020.52   234.1 1006.01   263.3  991.31   282.8  977.86   292.6  974.16
   341.3  962.77     467  954.48   477.7  954.40     482  954.63   497.0  958.46
   506.6  964.70   516.3  967.79   535.5  980.23   545.2  983.25   564.4  993.82
   574.1  996.60   641.5 1033.12   660.7 1045.20   689.6 1058.66   728.2 1070.55
   766.7 1078.79   814.9 1098.60   843.7 1107.15   872.6 1113.06   920.8 1119.09
#Mann= 3 , 0 , 0
       0     0.1       0     467   0.045       0     482     0.1       0
Bank Sta=     467,     482
Exp/Cntr=0.3,0.1

Type RM Length L Ch R = 1 ,1925.4,365.13,370.262,375.394
XS GIS Cut Line= 3
     1746847.055      372257.812     1746402.436      372162.240
     1745953.005      372085.494
#Sta/Elev= 30
       0 1116.38    29.0 1108.64    48.4 1099.16    58.1 1097.37    77.4 1089.76
   154.8 1065.60   203.2 1046.05   212.9 1043.89   232.2 1034.88   241.9 1033.13
   261.3 1023.59   270.9 1021.26   290.3 1012.57   300.0 1010.75   367.7  978.22
   387.0  966.62   435.4  957.28   549.8  952.06   551.8  952.05   564.8  953.81
   590.6  960.07   600.3  966.54   610.0  970.00   629.4  985.61   677.9 1015.84
   697.3 1030.48   726.4 1046.42   765.2 1062.71   862.2 1095.05   910.7 1113.01
#Mann= 3 , 0 , 0
       0     0.1       0   549.8   0.045       0   564.8     0.1       0
Bank Sta=   549.8,   564.8
Exp/Cntr=0.3,0.1

Type RM Length L Ch R = 1 ,1555.1,418.314,417.798,417.282
XS GIS Cut Line= 3
     1746846.652      372041.042     1746444.830      371827.585
     1746043.008      371614.128
#Sta/Elev= 30
       0 1110.34    96.8 1078.91   135.5 1063.71   154.9 1053.25   164.6 1050.90
   183.9 1040.21   222.7 1022.36   232.3 1019.73   271.1 1000.81   300.1  980.31
   329.1  963.98   367.9  952.86     444  945.81   445.3  945.77     459  946.46
   513.1  953.00   542.1  960.76   590.5  986.83   600.2  993.78   638.9 1012.59
   706.7 1043.72   755.1 1062.87   774.5 1073.44   793.8 1079.52   813.2 1089.92
   822.9 1092.33   842.2 1103.36   881.0 1120.24   890.6 1122.45   910.0 1132.49
#Mann= 3 , 0 , 0
       0     0.1       0     444   0.045       0     459     0.1       0
Bank Sta=     444,     459
Exp/Cntr=0.3,0.1

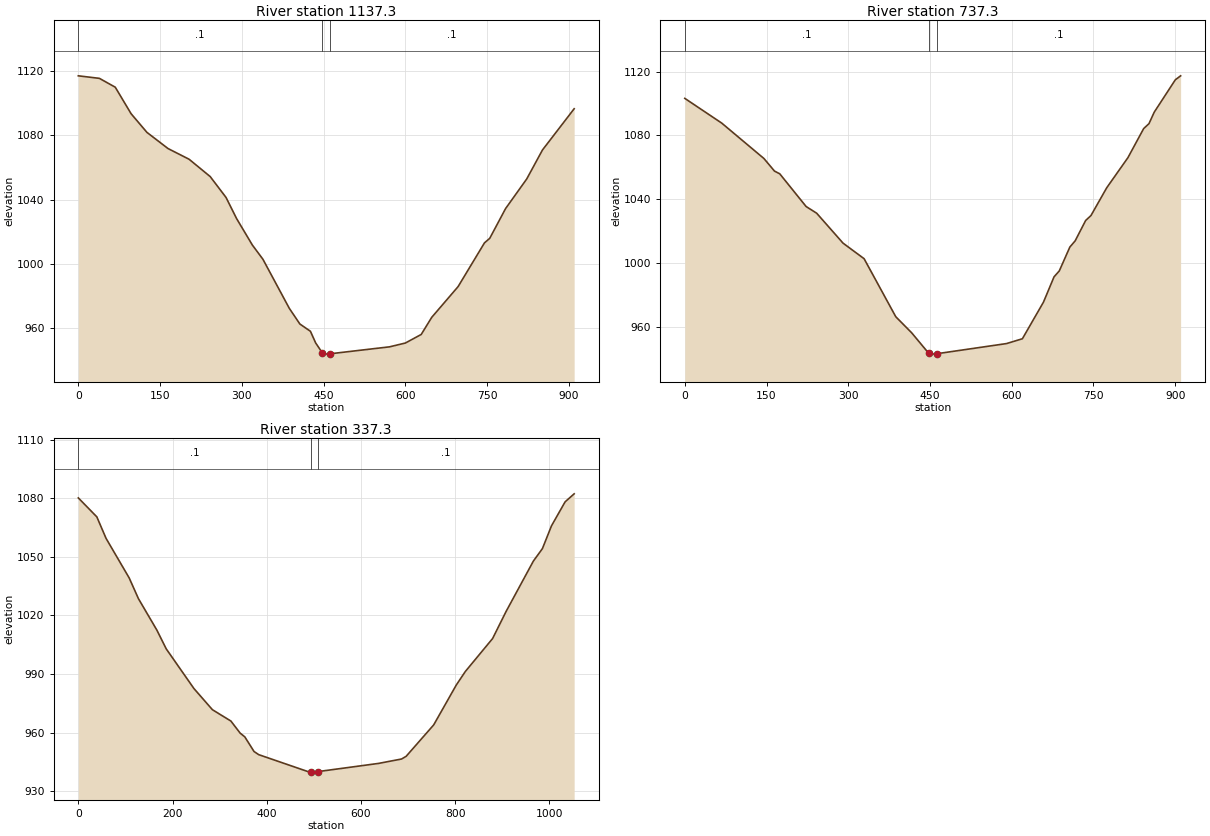
Type RM Length L Ch R = 1 ,1137.3,401.09,400,398.91
XS GIS Cut Line= 3
     1747126.821      371682.638     1746703.658      371515.433
     1746280.494      371348.227
#Sta/Elev= 30
       0 1116.86    38.7 1115.29    67.8 1109.79    96.8 1093.35   125.9 1081.75
   164.6 1071.71   203.3 1065.06   242.0 1054.31   271.1 1041.34   290.4 1028.26
   319.5 1011.75   338.8 1002.96   387.2  972.50   406.6  962.77   426.0  958.24
   435.6  950.99   447.5  945.02   455.0  944.06   462.5  944.29   571.2  948.59
   600.2  950.95   629.3  956.27   648.6  966.90   697.0  985.98   745.4 1013.14
   755.1 1015.98   784.1 1034.41   822.9 1052.79   851.9 1070.84   910.0 1096.41
#Mann= 3 , 0 , 0
       0     0.1       0   447.5   0.045       0   462.5     0.1       0
Bank Sta=   447.5,   462.5
Exp/Cntr=0.3,0.1

Type RM Length L Ch R = 1 ,737.3,402.472,400,394.654
XS GIS Cut Line= 3
     1747250.559      371279.705     1746819.791      371133.201
     1746389.022      370986.697
#Sta/Elev= 30
       0 1103.24    67.8 1087.73   145.2 1065.54   164.6 1057.65   174.3 1055.93
   222.7 1035.41   242.0 1031.24   290.4 1012.47   329.1 1002.69   387.2  966.32
   416.3  956.26   447.5  943.46   455.0  942.86   462.5  943.11   590.5  949.48
   619.6  952.50   658.3  975.47   677.7  991.34   687.3  995.03   706.7 1010.00
   716.4 1013.86   735.7 1026.67   745.4 1029.74   774.5 1047.25   813.2 1066.01
   842.2 1084.31   851.9 1087.37   861.6 1094.61   900.3 1114.90   910.0 1117.38
#Mann= 3 , 0 , 0
       0     0.1       0   447.5   0.045       0   462.5     0.1       0
Bank Sta=   447.5,   462.5
Exp/Cntr=0.3,0.1

Type RM Length L Ch R = 1 ,337.3,335.937,337.305,341.547
XS GIS Cut Line= 4
     1747398.445      370852.420     1746909.501      370744.387
     1746666.283      370722.335     1746380.178      370836.257
#Sta/Elev= 30
       0 1080.18    39.3 1070.48    58.9 1059.47   108.0 1039.21   127.6 1028.62
   166.9 1012.45   186.5 1002.96   245.5  982.58   284.7  971.76   324.0  965.94
   343.6  959.77   353.5  957.85   373.1  950.36   382.9  948.75   490.9  939.79
   493.2  939.81   508.2  940.04   637.5  944.25   686.3  946.50   696.1  947.88
   754.6  963.96   802.7  984.43   821.9  991.34   879.7 1008.18   908.6 1022.16
   966.3 1047.84   985.5 1054.23  1004.8 1065.91  1033.7 1078.18  1052.9 1082.28
#Mann= 3 , 0 , 0
       0     0.1       0   493.2   0.045       0   508.2     0.1       0
Bank Sta=   493.2,   508.2
Exp/Cntr=0.3,0.1